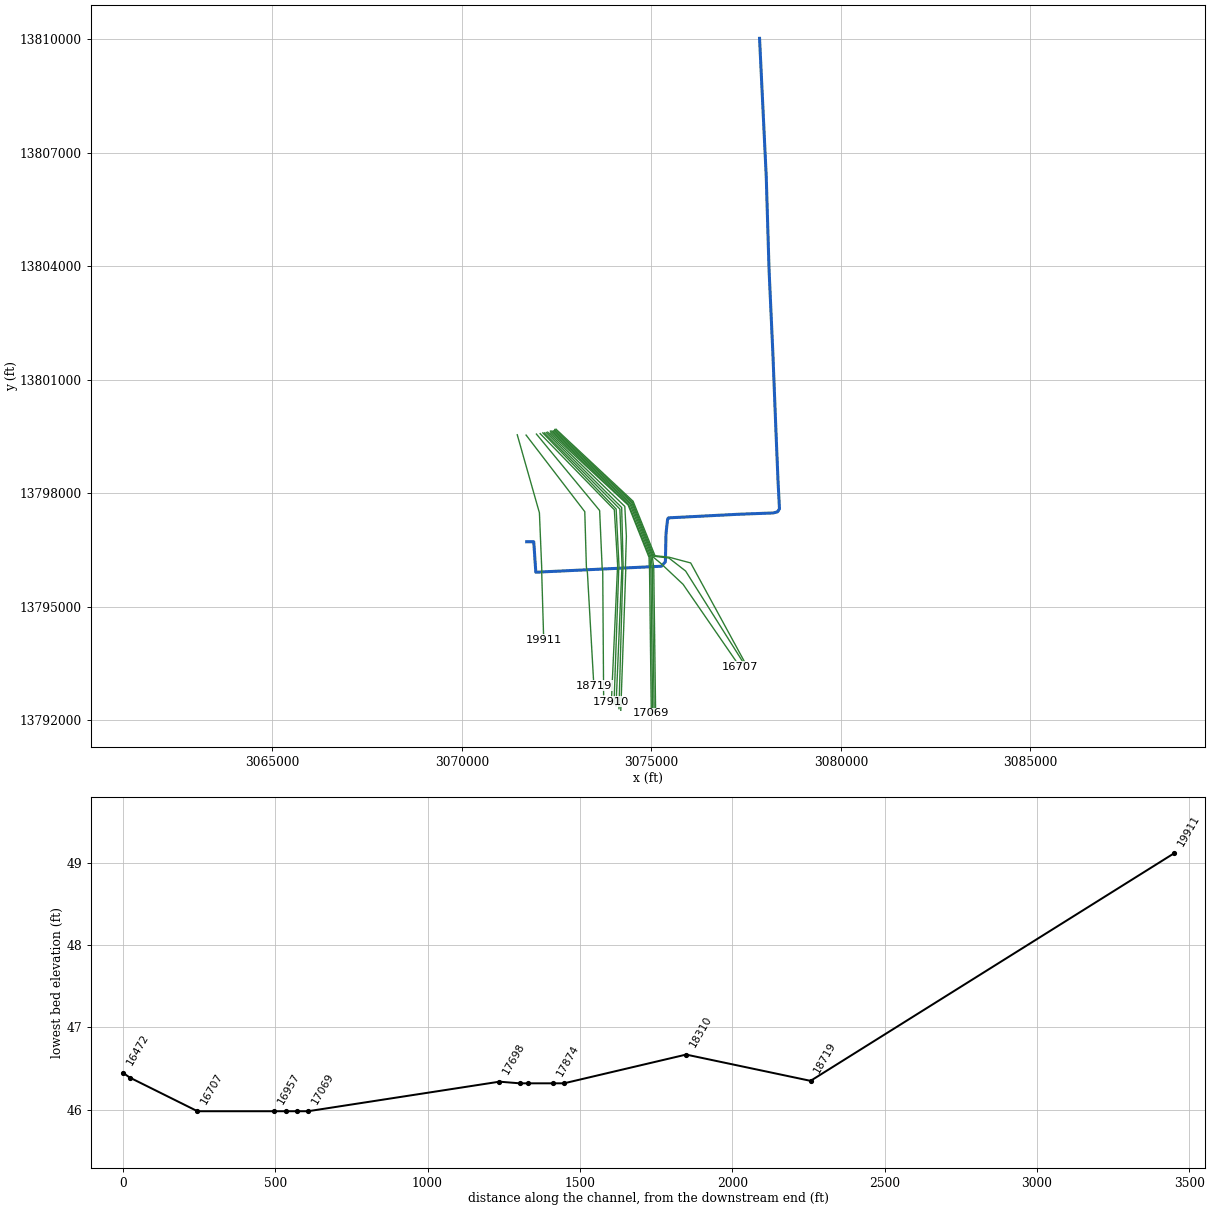
--- D140-00-00.prj (project) ---

Proj Title=D140-00-00
Current Plan=p06
Default Exp/Contr=.3,.1
English Units
Geom File=g02
Flow File=f05
Flow File=f06
Flow File=f03
Plan File=p06
Plan File=p08
Plan File=p04
Y Axis Title=Elevation (
X Axis Title(PF)=STATION
X Axis Title(XS)=Station
BEGIN DESCRIPTION:
Brays Bayou Watershed
Fondren Diversion Channel
HCFCD Unit D140-00-00
Flood Hazard & Floodway Model
10, 2, 1, 0.2% Event
Filename D140.prj
Prepared by: Dodson & Associates, Inc.   Date: September 2003
Reviewed by:____________________	 Date:_________
STATUS (Final RAS, SVSQ
FOR FLOOD HARZARD RECOVERY DATA ONLY,03/02/2004
Will Be Voided Upon Release of The Preliminary DFIRM
END DESCRIPTION:
DSS Export Rating Curves= 0
DSS Export Rating Curve Sorted= 0
DSS Export Volume Flow Curves= 0
DXF OffsetX= 0
DXF OffsetY= 0
DXF ScaleX= 1
DXF ScaleY= 10

--- D140-00-00.p06 (plan) ---

Plan Title=FEMA Effective June 2007
Version=Version 3.0.1  Mar 2001
Short Identifier=FEMAeff0607
Geom File=g02
Flow File=f05
Subcritical Flow
K Sum by GR= 0
Std Step Tol= 0.01
Critical Tol= 0.01
Num of Std Step Trials= 20
Max Error Tol= 0.3
Flow Tol Ratio= 0.001
Split Flow NTrial= 30
Split Flow Tol= 0.02
Split Flow Ratio= 0.02
Log Output Level= 0
Friction Slope Method= 2
Unsteady Friction Slope Method= 2
Secant Critical Depth
Global Vel Dist= 0 , 0 , 0
Global Log Level= 0
CheckData=True
Encroach Param=-1 ,0,0, 0
Computation Interval=1HOUR
Output Interval=1HOUR
Run HTab= 0
Run UNet= 0
Run PostProcess= 0
UNET Theta= 1
UNET ZTol= 0.02
UNET ZSATol= 0.1
UNET MxIter= 20
UNET MaxInSteps= 20
UNET DtIC= 0
UNET DtMin= 0
UNET MaxCRTS= 20
UNET WFStab= 2
UNET SFStab= 1
UNET WFX= 1
UNET SFX= 1
UNET Convert EG Bridges=-1
UNET Use Existing IB Tables=-1
Instantaneous Interval=1HOUR
Write IC File= 0
Write Velocity= 0
Write Detailed= 0

--- D140-00-00.p04 (plan) ---

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Plan Title=Storage Routing
Short Identifier=Store_Rout
Geom File=g02
Flow File=f03

--- D140-00-00.p08 (plan) ---

Plan Title=Floodway
Version=Version 3.0.1  Mar 2001
Short Identifier=Floodway0607
Geom File=g02
Flow File=f06
Subcritical Flow
K Sum by GR= 0
Std Step Tol= 0.01
Critical Tol= 0.01
Num of Std Step Trials= 20
Max Error Tol= 0.3
Flow Tol Ratio= 0.001
Split Flow NTrial= 30
Split Flow Tol= 0.02
Split Flow Ratio= 0.02
Log Output Level= 0
Friction Slope Method= 2
Unsteady Friction Slope Method= 2
Secant Critical Depth
Global Vel Dist= 0 , 0 , 0
Global Log Level= 0
CheckData=True
Encroach Param=-1 ,0,0, 2
Encroach River=D140-00-00
Encroach Reach=Reach 0
Encroach Node=19911
       1 3629.14  3758.8
Encroach Node=18719
       1 4031.36 4135.94
Encroach Node=18310
       1 4138.32 4209.87
Encroach Node=17910
       1 4341.88 4409.39
Encroach Node=17874
       1 4343.88 4411.39
Encroach Node=17837
       1 4343.88 4450.25
Encroach Node=17793
       1 4381.88 4450.25
Encroach Node=17764
       1 4394.88 4462.39
Encroach Node=17698
       1 4442.82 4509.21
Encroach Node=17069
       1 4525.43 4594.99
Encroach Node=17034
       1 4574.43  4642.4
Encroach Node=17013
       1 4571.43  4642.4
Encroach Node=16996
       1 4571.43  4639.4
Encroach Node=16957
       1 4569.43 4639.43
Encroach Node=16707
       1 4628.43  4696.4
Encroach Node=16495
       1 4580.93 4726.34
Encroach Node=16480
       1 4536.82 4726.34
Encroach Node=16472
       1 4536.82  4689.3
Encroach Node=16368
       1 4451.25 4586.27
Encroach Node=16152
       1 4317.17 4466.49
Encroach Node=15749
       1 3968.58 4121.17
Encroach Node=15538
       1 3779.65 3947.33
Encroach Node=14872
       1 4215.48  4380.9
Encroach Node=14119
       1 4813.05 4976.46
Encroach Node=13655
       1 5285.76 5449.67
Encroach Node=13551
       1 5409.74 5615.16
Encroach Node=13459
       1 5482.23 5657.56
Encroach Node=13400
       1 5482.23 5766.56
Encroach Node=13347
       1 5605.22 5766.56
Encroach Node=13248
       1  5683.1 5898.92
Encroach Node=13169
       1 5751.04 5935.14
Encroach Node=12531
       1 6098.54 6239.68
Encroach Node=11781
       1 5850.75 6018.97
Encroach Node=11700
       1 5861.75 6024.35
Encroach Node=11650
       1 5810.64 6024.35
Encroach Node=11586
       1 5810.64 5952.35
Encroach Node=11502
       1 5771.64 5913.35
Encroach Node=10912
       1 5567.36 5710.96
Encroach Node=9302
       1 5319.12 5488.38
Encroach Node=9187
       1 5807.81 5979.38
Encroach Node=9164
       1 5807.81 6243.38
Encroach Node=9145
       1 6074.12 6243.38
Encroach Node=9025
       1 6057.43 6238.38
Encroach Node=8552
       1 6052.59 6218.37
Encroach Node=7849
       1 6007.11 6192.22
Encroach Node=7530
       1 5997.34  6180.9
Encroach Node=7427
       1 6040.78 6187.44
Encroach Node=7378
       1 6040.78 6187.44
Encroach Node=7329
       1 6041.78  6179.9
Encroach Node=7221
       1 6038.78  6176.9
Encroach Node=6446
       1 5999.84 6151.15
Encroach Node=5555
       1 5599.83 5799.32
Encroach Node=5032
       1 5431.82 5656.71
Encroach Node=4873
       1 5421.52 5637.99
Encroach Node=4862
       1 5419.17 5646.61
Encroach Node=4853
       1 5419.17 5646.61
Encroach Node=4694
       1 5396.86 5621.91
Encroach Node=4636
       1 5398.76  5623.8
Encroach Node=3724
       1 5123.98 5354.92
Encroach Node=3589
       1 3969.82 4147.26
Encroach Node=3546
       1  3743.6 4147.26
Encroach Node=3504
       1  3743.6 3920.26
Encroach Node=3392
       1  193.01  475.86
Encroach Node=3104
       1  263.09  435.69
Encroach Node=2212
       1  257.75  458.35
Encroach Node=2137
       1  191.12  454.48
Encroach Node=2011
       1  266.29  428.58
Encroach Node=1970
       1  266.29  428.58
Encroach Node=1931
       1  266.29  428.58
Encroach Node=1802
       1  261.29  423.58
Encroach Node=1374
       1  248.67  421.73
Encroach Node=837
       1  242.94  457.37
Encroach Node=370
       1  234.48  445.74
Encroach Node=295
       1  234.48  445.74
Encroach Node=268
       1  238.06  436.64
Encroach Node=178
       1  238.06  436.64
Encroach Node=122
       1  168.29  361.89
Encroach Node=102
       1  168.29  361.89
Encroach Reach=D140-00-00_0001
Encroach Node=19911
       1 3629.14  3758.8
Encroach Node=18719
       1 4031.36 4135.94
Encroach Node=18310
       1 4138.32 4209.87
Encroach Node=17910
       1 4341.88 4409.39
Encroach Node=17874
       1 4343.88 4411.39
Encroach Node=17837
       1 4343.88 4450.25
Encroach Node=17793
       1 4381.88 4450.25
Encroach Node=17764
       1 4394.88 4462.39
Encroach Node=17698
       1 4442.82 4509.21
Encroach Node=17069
       1 4525.43 4594.99
Encroach Node=17034
       1 4574.43  4642.4
Encroach Node=17013
       1 4571.43  4642.4
Encroach Node=16996
       1 4571.43  4639.4
Encroach Node=16957
       1 4569.43 4639.43
Encroach Node=16707
       1 4628.43  4696.4
Encroach Node=16495
       1 4580.93 4726.34
Encroach Node=16480
       1 4536.82 4726.34
Encroach Node=16472
       1 4536.82  4689.3
Encroach Node=16368
       1 4451.25 4586.27
Encroach Node=16152
       1 4317.17 4466.49
Encroach Node=15749
       1 3968.58 4121.17
Encroach Node=15538
       1 3779.65 3947.33
Encroach Node=14872
       1 4215.48  4380.9
Encroach Node=14119
       1 4813.05 4976.46
Encroach Node=13655
       1 5285.76 5449.67
Encroach Node=13551
       1 5409.74 5615.16
Encroach Node=13459
       1 5482.23 5657.56
Encroach Node=13400
       1 5482.23 5766.56
Encroach Node=13347
       1 5605.22 5766.56
Encroach Node=13248
       1  5683.1 5898.92
Encroach Node=13169
       1 5751.04 5935.14
Encroach Node=12531
       1 6098.54 6239.68
Encroach Node=11781
       1 5850.75 6018.97
Encroach Node=11700
       1 5861.75 6024.35
Encroach Node=11650
       1 5810.64 6024.35
Encroach Node=11586
       1 5810.64 5952.35
Encroach Node=11502
       1 5771.64 5913.35
Encroach Node=10912
       1 5567.36 5710.96
Encroach Node=9302
       1 5319.12 5488.38
Encroach Node=9187
       1 5807.81 5979.38
Encroach Node=9164
       1 5807.81 6243.38
Encroach Node=9145
       1 6074.12 6243.38
Encroach Node=9025
       1 6057.43 6238.38
Encroach Node=8552
       1 6052.59 6218.37
Encroach Node=7849
       1 6007.11 6192.22
Encroach Node=7530
       1 5997.34  6180.9
Encroach Node=7427
       1 6040.78 6187.44
Encroach Node=7378
       1 6040.78 6187.44
Encroach Node=7329
       1 6041.78  6179.9
Encroach Node=7221
       1 6038.78  6176.9
Encroach Node=6446
       1 5999.84 6151.15
Encroach Node=5555
       1 5599.83 5799.32
Encroach Node=5032
       1 5431.82 5656.71
Encroach Node=4873
       1 5421.52 5637.99
Encroach Node=4862
       1 5419.17 5646.61
Encroach Node=4853
       1 5419.17 5646.61
Encroach Node=4694
       1 5396.86 5621.91
Encroach Node=4636
       1 5398.76  5623.8
Encroach Node=3724
       1 5123.98 5354.92
Encroach Node=3589
       1 3969.82 4147.26
Encroach Node=3546
       1  3743.6 4147.26
Encroach Node=3504
       1  3743.6 3920.26
Encroach Node=3392
       1  193.01  475.86
Encroach Node=3104
       1  263.09  435.69
Encroach Node=2212
       1  257.75  458.35
Encroach Node=2137
       1  191.12  454.48
Encroach Node=2011
       1  266.29  428.58
Encroach Node=1970
       1  266.29  428.58
Encroach Node=1931
       1  266.29  428.58
Encroach Node=1802
       1  261.29  423.58
Encroach Node=1374
       1  248.67  421.73
Encroach Node=837
       1  242.94  457.37
Encroach Node=370
       1  234.48  445.74
Encroach Node=295
       1  234.48  445.74
Encroach Node=268
       1  238.06  436.64
Encroach Node=178
       1  238.06  436.64
Encroach Node=122
       1  168.29  361.89
Encroach Node=102
       1  168.29  361.89
Computation Interval=1HOUR
Output Interval=1HOUR
Run HTab= 0
Run UNet= 0
Run PostProcess= 0
UNET Theta= 1
UNET ZTol= 0.02
UNET ZSATol= 0.1
UNET MxIter= 20
UNET MaxInSteps= 20
UNET DtIC= 0
UNET DtMin= 0
UNET MaxCRTS= 20
UNET WFStab= 2
UNET SFStab= 1
UNET WFX= 1
UNET SFX= 1
UNET Convert EG Bridges=-1
UNET Use Existing IB Tables=-1
Instantaneous Interval=1HOUR
Write IC File= 0
Write Velocity= 0
Write Detailed= 0

--- D140-00-00.f05 (steady flow) ---

Flow Title=FEMA Effective June 2007
Version=Version 3.0.1  Mar 2001
Number of Profiles= 4
Profile Names=10PCT_10yr,2PCT_50yr,1PCT_100yr,0.2PCT_500yr
River Rch & RM=D140-00-00,D140-00-00_0001 ,19911
    1491    2235    2609    3669
River Rch & RM=D140-00-00,D140-00-00_0001 ,18719
    1573    2359    2751    3846
River Rch & RM=D140-00-00,D140-00-00_0001 ,17698
    1634    2453    2858    3980
River Rch & RM=D140-00-00,D140-00-00_0001 ,16957
    1777    2671    3108    4290
River Rch & RM=D140-00-00,D140-00-00_0001 ,15538
    1893    2848    3310    4539
River Rch & RM=D140-00-00,D140-00-00_0001 ,14119
    1989    2995    3477    4743
River Rch & RM=D140-00-00,D140-00-00_0001 ,13169
    2236    3373    3908    5265
River Rch & RM=D140-00-00,D140-00-00_0001 ,10912
    2574    3870    4356    5555
River Rch & RM=D140-00-00,D140-00-00_0001 ,9025
    2809    4216    4661    5744
River Rch & RM=D140-00-00,D140-00-00_0001 ,7849
    2944    4413    4832    5848
River Rch & RM=D140-00-00,D140-00-00_0001 ,7221
    3072    3885    4183    5033
River Rch & RM=D140-00-00,D140-00-00_0001 ,5555
    3152    4009    4331    5228
River Rch & RM=D140-00-00,D140-00-00_0001 ,4636
    3291    4224    4590    5569
River Rch & RM=D140-00-00,D140-00-00_0001 ,3104
    3456    4480    4901    5980
River Rch & RM=D140-00-00,D140-00-00_0001 ,1374
    3592    4695    5163    6329
Boundary for River Rch & Prof#=D140-00-00,D140-00-00_0001 , 1
Up Type= 0
Dn Type= 3
Dn Slope=.0006
Boundary for River Rch & Prof#=D140-00-00,D140-00-00_0001 , 2
Up Type= 0
Dn Type= 3
Dn Slope=.0006
Boundary for River Rch & Prof#=D140-00-00,D140-00-00_0001 , 3
Up Type= 0
Dn Type= 3
Dn Slope=.0006
Boundary for River Rch & Prof#=D140-00-00,D140-00-00_0001 , 4
Up Type= 0
Dn Type= 3
Dn Slope=.0006
DSS Import GetInterval= 0
DSS Import GetPeak= 0
DSS Import FillOption= 0

--- D140-00-00.f03 (steady flow) ---

Flow Title=Storage Routing
Version=Version 3.0.1  Mar 2001
Number of Profiles= 8
Profile Names=0.1,0.2,0.4,0.6,0.8,1.0,1.2,1.5
River Rch & RM=D140-00-00,D140-00-00_0001 ,19911
     391     782    1564    2346    3128    3910    4692    5865
River Rch & RM=D140-00-00,D140-00-00_0001 ,10912
     432     864    1728    2592    3456    4320    5184    6480
River Rch & RM=D140-00-00,D140-00-00_0001 ,7221
     517    1034    2068    3102    4136    5170    6204    7755
Boundary for River Rch & Prof#=D140-00-00,D140-00-00_0001 , 1
Up Type= 0
Dn Type= 3
Dn Slope=.0006
Boundary for River Rch & Prof#=D140-00-00,D140-00-00_0001 , 2
Up Type= 0
Dn Type= 3
Dn Slope=.0006
Boundary for River Rch & Prof#=D140-00-00,D140-00-00_0001 , 3
Up Type= 0
Dn Type= 3
Dn Slope=.0006
Boundary for River Rch & Prof#=D140-00-00,D140-00-00_0001 , 4
Up Type= 0
Dn Type= 3
Dn Slope=.0006
Boundary for River Rch & Prof#=D140-00-00,D140-00-00_0001 , 5
Up Type= 0
Dn Type= 3
Dn Slope=.0006
Boundary for River Rch & Prof#=D140-00-00,D140-00-00_0001 , 6
Up Type= 0
Dn Type= 3
Dn Slope=.0006
Boundary for River Rch & Prof#=D140-00-00,D140-00-00_0001 , 7
Up Type= 0
Dn Type= 3
Dn Slope=.0006
Boundary for River Rch & Prof#=D140-00-00,D140-00-00_0001 , 8
Up Type= 0
Dn Type= 3
Dn Slope=.0006
DSS Import GetInterval= 0
DSS Import GetPeak= 0
DSS Import FillOption= 0

--- D140-00-00.f06 (steady flow) ---

Flow Title=Floodway
Version=Version 3.0.1  Mar 2001
Number of Profiles= 2
Profile Names=1PCT_100yr,1PCTFloodway_100yrFW
River Rch & RM=D140-00-00,D140-00-00_0001 ,19911
    2609    2609
River Rch & RM=D140-00-00,D140-00-00_0001 ,18719
    2751    2751
River Rch & RM=D140-00-00,D140-00-00_0001 ,17698
    2858    2858
River Rch & RM=D140-00-00,D140-00-00_0001 ,16957
    3108    3108
River Rch & RM=D140-00-00,D140-00-00_0001 ,15538
    3310    3310
River Rch & RM=D140-00-00,D140-00-00_0001 ,14119
    3477    3477
River Rch & RM=D140-00-00,D140-00-00_0001 ,13169
    3908    3908
River Rch & RM=D140-00-00,D140-00-00_0001 ,10912
    4356    4356
River Rch & RM=D140-00-00,D140-00-00_0001 ,9025
    4661    4661
River Rch & RM=D140-00-00,D140-00-00_0001 ,7849
    4832    4832
River Rch & RM=D140-00-00,D140-00-00_0001 ,7221
    4183    4183
River Rch & RM=D140-00-00,D140-00-00_0001 ,5555
    4331    4331
River Rch & RM=D140-00-00,D140-00-00_0001 ,4636
    4590    4590
River Rch & RM=D140-00-00,D140-00-00_0001 ,3104
    4901    4901
River Rch & RM=D140-00-00,D140-00-00_0001 ,1374
    5163    5163
Boundary for River Rch & Prof#=D140-00-00,D140-00-00_0001 , 1
Up Type= 0
Dn Type= 1
Dn Known WS=53.88
Boundary for River Rch & Prof#=D140-00-00,D140-00-00_0001 , 2
Up Type= 0
Dn Type= 1
Dn Known WS=53.88
DSS Import GetInterval= 0
DSS Import GetPeak= 0
DSS Import FillOption= 0

--- D140-00-00.g02 (geometry) ---

Geom Title=D140-00-00 June 2007
Version=Version 3.0.1  Mar 2001

River Reach=D140-00-00      ,D140-00-00_0001
Reach XY= 30
      3071706.52    13796722.829     3071894.972    13796723.129
     3071949.281    13795918.584       3072232.5    13795932.093
     3075262.379    13796076.601     3075367.331    13796191.948
     3075384.486    13796941.507     3075419.167    13797263.673
     3075428.661    13797328.238     3075452.922    13797355.119
       3077287.5    13797449.718     3077294.597    13797450.083
       3078202.5    13797484.273     3078216.096    13797484.784
     3078329.883    13797516.282     3078377.086    13797595.607
      3078339.52    13798324.134     3078285.743    13799615.691
     3078219.801      13801282.5     3078214.006    13801429.006
      3078210.58     13801515.58     3078201.249    13801751.467
     3078200.059      13801777.5     3078198.201    13801818.201
     3078194.269    13801904.269     3078187.063    13802062.063
     3078183.131    13802148.131     3078101.979    13803924.927
     3078028.667    13806366.104     3077851.864    13810027.468

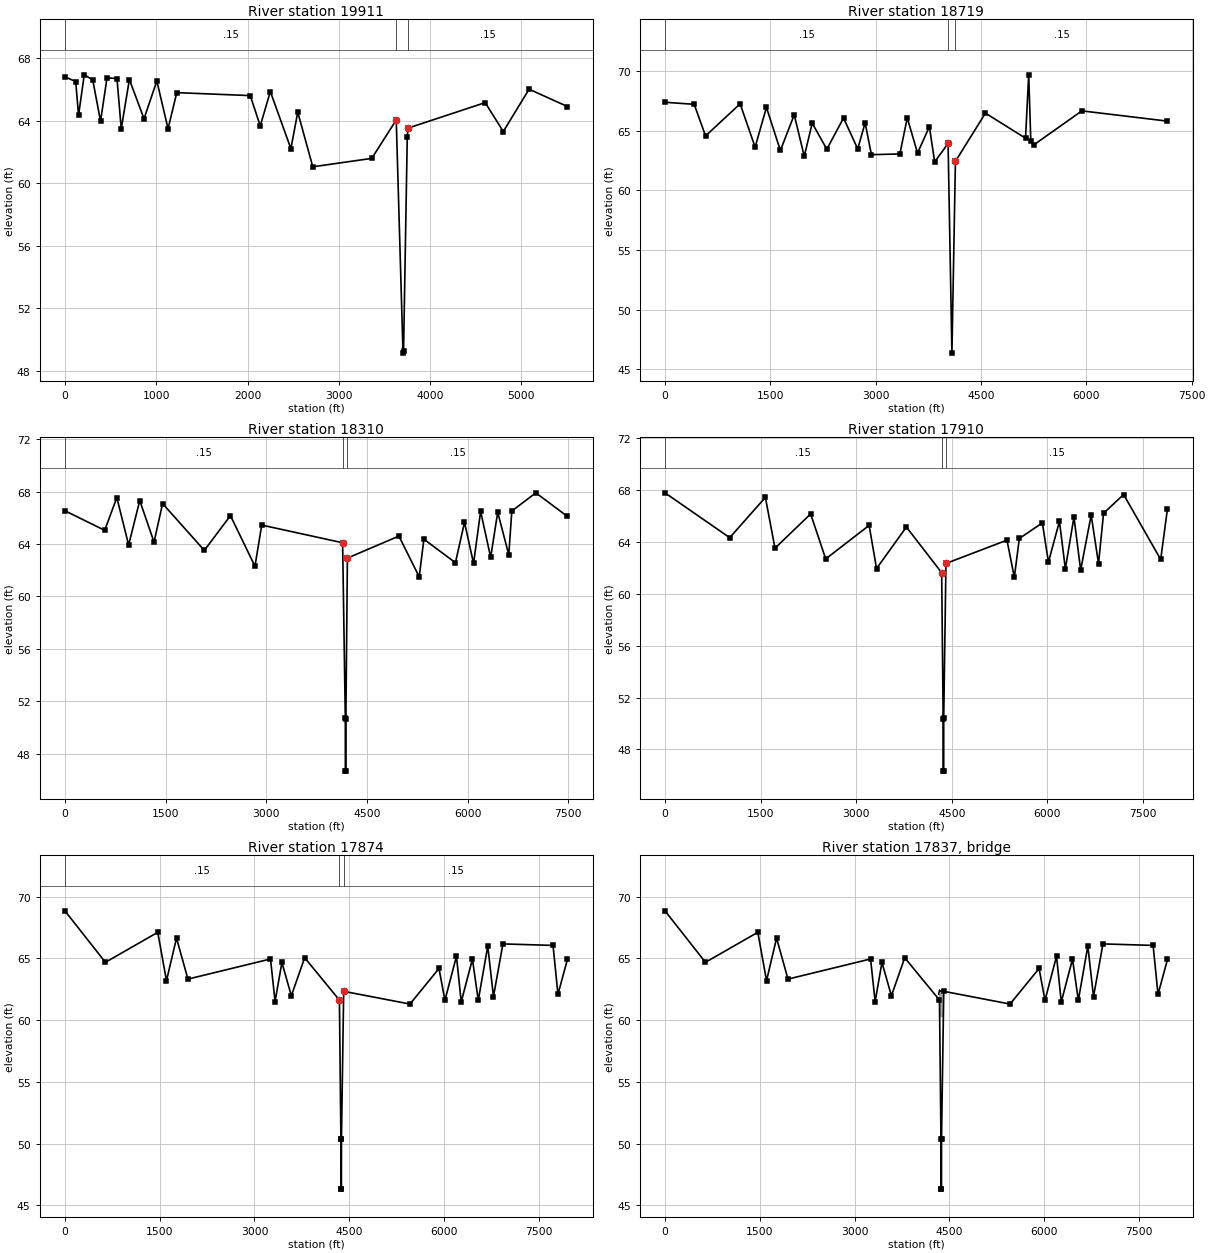
Type RM Length L Ch R = 1 ,19911   ,1179.38,1192.44,1207.88
BEGIN DESCRIPTION:
19911.20  Survey
END DESCRIPTION:
XS GIS Cut Line= 5
      3071459.42    13799551.187     3072044.084     13797488.65
     3072105.859    13796004.593     3072105.859    13795874.934
     3072157.377    13794130.367
#Sta/Elev= 30
       0   66.81  118.17   66.51  149.35   64.35  211.71   66.94  304.63   66.62
  390.15   63.97  461.17   66.75  570.31    66.7  617.08   63.48  705.99   66.64
  866.54   64.13 1006.85   66.55 1129.65   63.49 1225.13    65.8 2030.07   65.61
  2139.4   63.67 2250.04   65.87 2475.24   62.21  2550.3   64.55  2715.1   61.05
 3361.01   61.59 3629.14   64.05 3703.32   49.12 3709.17   49.23 3749.91   62.98
  3758.8   63.53 4603.32   65.16 4801.69   63.31 5084.33   66.02 5504.13   64.91
#Mann= 3 , 0 , 0
       0     .15       0 3629.14     .04       0  3758.8     .15       0
#XS Ineff= 2 , 0
       0    3618            3784       0
Permanent Ineff=
       T       T
Bank Sta=3629.14,3758.8
XS Rating Curve= 0
Exp/Cntr=.3,.1

Type RM Length L Ch R = 1 ,18719   ,413.99,408.38,400.34
BEGIN DESCRIPTION:
18718.76  Survey
END DESCRIPTION:
XS GIS Cut Line= 6
     3071692.704    13799542.854     3073241.209    13797518.439
     3073283.249    13796059.791     3073310.595    13795906.193
     3073441.919    13793597.123     3073480.507    13792919.374
#Sta/Elev= 30
       0   67.37  415.92    67.2  577.92   64.55 1070.14   67.24  1283.5   63.61
 1444.64   66.94 1643.45   63.33 1840.56   66.32 1983.38   62.84 2096.69   65.62
 2304.43   63.44 2542.65   66.05 2744.77   63.46 2849.82   65.65 2939.85   62.98
 3345.02   63.04 3450.06   66.07 3596.24   63.11 3765.19   65.33 3840.23   62.37
 4031.36   63.92 4086.03   46.35 4135.94   62.42 4563.36   66.46 5134.28   64.36
 5179.35   69.67  5209.4   64.14 5254.25   63.81 5936.82   66.65 7155.67   65.79
#Mann= 3 , 0 , 0
       0     .15       0 4031.36     .04       0 4135.94     .15       0
#XS Ineff= 2 , 0
       0    4008            4157       0
Permanent Ineff=
       T       T
Bank Sta=4031.36,4135.94
XS Rating Curve= 0
Exp/Cntr=.3,.1

Type RM Length L Ch R = 1 ,18310   ,409.78,400.82,381.5
BEGIN DESCRIPTION:
18310.38  Survey
END DESCRIPTION:
XS GIS Cut Line= 5
     3071965.001    13799569.912     3073632.948     13797549.09
      3073699.79    13796029.914     3073714.546    13795949.608
     3073737.974    13792683.728
#Sta/Elev= 30
       0   66.53  593.07   65.04  773.69   67.54  949.67   63.92 1115.16   67.31
 1328.26   64.14 1455.35   67.08 2077.74   63.51 2466.73   66.16 2832.06    62.3
 2932.96   65.44 4138.32   64.09 4178.52   50.69 4179.18   46.67 4186.45   46.67
 4187.11   50.68 4209.87   62.92 4977.23    64.6 5279.69   61.49 5349.56   64.36
 5819.71   62.57 5954.71   65.65 6089.71   62.51 6194.72   66.49 6344.72   62.98
 6449.72   66.42 6614.73   63.17 6659.73   66.51 7017.64    67.9 7488.52    66.1
#Mann= 3 , 0 , 0
       0     .15       0 4138.32    .017       0 4209.87     .15       0
#XS Ineff= 2 , 0
       0    4133            4210       0
Permanent Ineff=
       T       T
Bank Sta=4138.32,4209.87
XS Rating Curve= 0
Exp/Cntr=.3,.1

Type RM Length L Ch R = 1 ,17910   ,35.57,35.33,36.4
BEGIN DESCRIPTION:
 17909.56
END DESCRIPTION:
XS GIS Cut Line= 5
     3072064.177    13799580.929     3074020.709    13797568.578
     3074109.496    13796069.256      3074101.56     13795980.36
     3073942.836    13792496.228
#Sta/Elev= 30
       0   67.79 1015.97   64.33 1575.58   67.44  1726.2   63.52 2285.67   66.16
 2522.28   62.69 3203.47   65.28 3320.12   61.95 3788.26   65.15 4341.88   61.63
 4365.26   50.37 4366.19   46.32 4373.26   46.32 4374.19   50.39 4409.39   62.34
 5366.76   64.14 5482.17   61.27 5560.83   64.27 5922.34   65.47 6017.06   62.44
 6190.12   65.59 6282.71   61.93 6417.85   65.92 6522.96   61.83 6688.13   66.07
 6803.68   62.33 6882.34   66.21 7196.98   67.66 7779.08   62.65 7885.64   66.58
#Mann= 3 , 0 , 0
       0     .15       0 4341.88    .017       0 4409.39     .15       0
#XS Ineff= 2 , 0
       0    4318            4430       0
Permanent Ineff=
       T       T
Bank Sta=4341.88,4409.39
XS Rating Curve= 0
Exp/Cntr=.5,.3

Type RM Length L Ch R = 1 ,17874   ,81.49,81.6,80.44
BEGIN DESCRIPTION:
 17874.24
END DESCRIPTION:
XS GIS Cut Line= 5
     3072133.576    13799600.757     3074068.665    13797588.294
      3074144.44    13796067.096     3074136.504      13795978.2
     3074012.255    13792432.693
#Sta/Elev= 30
       0   68.86  640.48   64.69 1469.07   67.12 1606.98    63.2 1765.83   66.65
 1946.46   63.33 3253.24   64.96 3325.61   61.51 3433.46   64.68 3583.12   61.98
 3793.91   65.06 4343.88   61.63 4367.26   50.37 4368.19   46.32 4375.26   46.32
 4376.19   50.39 4411.39   62.34 5460.56   61.31 5919.92   64.19 6013.25   61.61
 6196.01   65.18 6271.06   61.48 6448.77   64.95 6541.22   61.61 6691.31   66.01
 6781.37   61.91 6930.95   66.18 7724.22   66.06 7801.99    62.1 7951.89   64.92
#Mann= 3 , 0 , 0
       0     .15       0 4343.88    .017       0 4411.39     .15       0
#XS Ineff= 2 , 0
       0    4320            4420       0
Permanent Ineff=
       T       T
Bank Sta=4343.88,4411.39
XS Rating Curve= 0
Exp/Cntr=.5,.3

Type RM Length L Ch R = 3 ,17837   ,,,
BEGIN DESCRIPTION:
McLain Bridge
END DESCRIPTION:
Bridge Culvert--1,0,-1,-1, 0
Deck Dist Width WeirC Skew NumUp NumDn MinLoCord MaxHiCord MaxSubmerge Is_Ogee
5,64,2.6,0, 8, 8, , , .95, 0, 0,0,,
    4330 4344.64 4352.33 4352.33 4374.83 4397.33 4397.33    4412
    62.1   62.45   62.37   62.37   62.36    62.3    62.3    62.3
       0       0       0   60.27   60.26    60.2       0       0
    4360 4382.64 4390.33 4390.33 4412.83 4435.33 4435.33    4450
   62.08   62.45   62.37   62.37   62.36    62.3    62.3    62.3
       0       0       0   60.27   60.26    60.2       0       0
BR Coef=-1 , 0 , 0 ,, 0 ,,,.8,-1,,0,
WSPro=,,,, 1 ,,,, 0 ,,,, 0 ,,,,-1 ,-1 ,-1 , 0 , 0 , 0 , 0 , 0
BC Design=,, 0 ,, 0 ,,,,,,

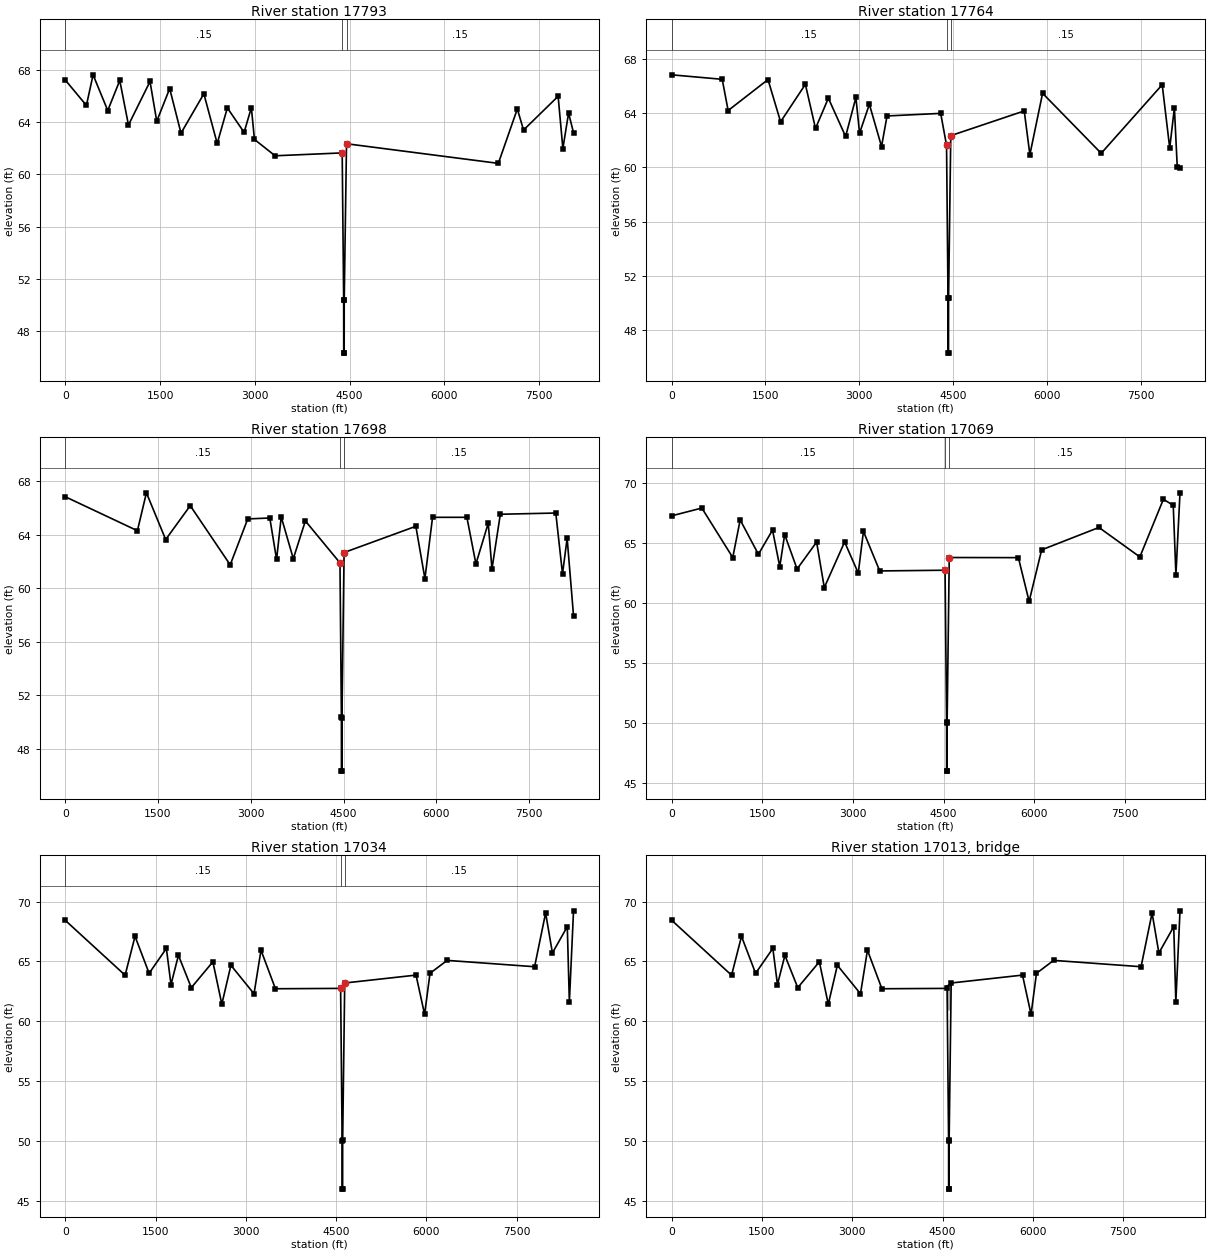
Type RM Length L Ch R = 1 ,17793   ,29.34,28.42,29.74
BEGIN DESCRIPTION:
17792.63  Survey
END DESCRIPTION:
XS GIS Cut Line= 5
     3072173.232    13799600.757     3074166.998    13797588.243
     3074225.156    13796062.106     3074217.221    13795973.209
     3074065.454    13792384.002
#Sta/Elev= 30
       0   67.21  335.38   65.26  440.95    67.6  673.21   64.87  863.25   67.17
 1000.68   63.76 1341.69   67.09 1448.26   64.05  1652.9   66.55 1831.89   63.14
 2193.47   66.15 2404.61   62.35 2565.08   65.07 2830.24    63.2 2944.96   65.09
 2993.76   62.66 3320.91   61.41 4381.88   61.63 4405.26   50.37 4406.19   46.32
 4413.26   46.32 4414.19   50.39 4450.25   62.33 6852.25   60.83 7152.51   64.99
 7251.25   63.38 7798.09   65.96 7873.16   61.96 7963.24   64.68  8041.8   63.17
#Mann= 3 , 0 , 0
       0     .15       0 4381.88    .017       0 4450.25     .15       0
#XS Ineff= 2 , 0
       0    4355            4455       0
Permanent Ineff=
       T       T
Bank Sta=4381.88,4450.25
XS Rating Curve= 0
Exp/Cntr=.5,.3

Type RM Length L Ch R = 1 ,17764   ,65.81,66.51,76.17
BEGIN DESCRIPTION:
 17764.22
END DESCRIPTION:
XS GIS Cut Line= 5
     3072222.802    13799610.671     3074214.444    13797627.832
     3074253.267    13796060.366     3074245.331     13795971.47
     3074142.884    13792313.134
#Sta/Elev= 30
       0   66.82  808.13   66.49  902.67   64.19 1539.99   66.47 1741.52   63.36
 2137.62   66.12 2299.65   62.87 2505.19    65.1 2780.97   62.28 2945.47   65.15
 3004.04   62.52 3160.83   64.65 3355.45   61.54  3443.3   63.79 4301.18   63.98
 4394.88   61.63 4418.26   50.37 4419.19   46.32 4426.26   46.32 4427.19   50.39
 4462.39   62.34 5636.92   64.16 5727.05   60.94 5930.24   65.46  6867.5   61.04
 7842.88   66.09 7962.93   61.43 8037.95   64.39 8082.97   60.06 8127.36   59.98
#Mann= 3 , 0 , 0
       0     .15       0 4394.88    .017       0 4462.39     .15       0
#XS Ineff= 2 , 0
       0    4370            4505       0
Permanent Ineff=
       T       T
Bank Sta=4394.88,4462.39
XS Rating Curve= 0
Exp/Cntr=.3,.1

Type RM Length L Ch R = 1 ,17698   ,624.09,628.37,632.66
BEGIN DESCRIPTION:
17697.70  Survey
END DESCRIPTION:
XS GIS Cut Line= 6
     3072262.459    13799620.585     3074296.887    13797657.709
     3074338.417    13796866.289      3074313.54    13796064.843
     3074322.177    13795977.675      3074190.81     13792269.27
#Sta/Elev= 30
       0   66.84 1167.29    64.3  1313.2   67.13 1624.69   63.64 2021.88   66.17
 2668.02   61.75 2951.44   65.18 3308.24   65.25 3417.99   62.15  3493.1   65.33
  3688.3   62.21  3883.4   65.03 4442.82    61.9 4466.04   50.41 4466.82   46.34
 4474.08   46.34 4474.86   50.34 4509.21   62.67 5669.81   64.63 5816.52   60.72
 5939.98    65.3 6495.33    65.3 6641.23   61.82 6840.54   64.86 6900.58   61.44
 7035.67   65.53 7932.76   65.62  8041.3   61.08 8116.34   63.73 8219.64   57.94
#Mann= 3 , 0 , 0
       0     .15       0 4442.82    .017       0 4509.21     .15       0
#XS Ineff= 2 , 0
       0    4390            4534       0
Permanent Ineff=
       T       T
Bank Sta=4442.82,4509.21
XS Rating Curve= 0
Exp/Cntr=.3,.1

Type RM Length L Ch R = 1 ,17069   ,30.07,35.03,35.09
BEGIN DESCRIPTION:
 17069.33
END DESCRIPTION:
XS GIS Cut Line= 6
     3072331.857    13799600.757     3074385.719    13797691.958
     3074937.277    13796309.471     3074942.353     13796087.64
     3074948.963    13796007.026     3074996.432    13792188.058
#Sta/Elev= 30
       0   67.29  499.17   67.94    1011   63.81 1133.98   66.95 1435.61   64.08
 1669.11    66.1 1789.27   63.05 1870.33   65.73 2075.96   62.85 2399.15    65.1
 2526.47    61.3 2862.53   65.11 3088.63   62.51 3174.27   65.99 3443.92   62.69
 4525.43   62.75 4550.59   50.02 4551.35   45.98 4558.66   45.98 4559.42   50.09
 4594.99   63.81 5739.06    63.8 5916.86   60.15  6124.3   64.45 7072.59   66.32
  7749.9   63.86 8139.41   68.67  8302.4   68.17 8346.85   62.37 8414.39   69.21
#Mann= 3 , 0 , 0
       0     .15       0 4525.43    .017       0 4594.99     .15       0
#XS Ineff= 2 , 0
       0    4470            4609       0
Permanent Ineff=
       T       T
Bank Sta=4525.43,4594.99
XS Rating Curve= 0
Exp/Cntr=.5,.3

Type RM Length L Ch R = 1 ,17034   ,34.45,38.74,38.71
BEGIN DESCRIPTION:
 17034.31
END DESCRIPTION:
XS GIS Cut Line= 6
     3072332.843    13799648.137     3074401.296    13797702.136
     3074961.677    13796309.474     3074977.315      13796089.6
     3074983.925    13796008.986     3075034.025    13792208.818
#Sta/Elev= 30
       0   68.44  994.95   63.85 1159.71    67.1 1393.86   64.01 1680.37   66.09
 1756.96   63.07 1880.53   65.51 2094.22   62.81  2452.7   64.97 2601.35   61.43
 2752.13   64.68    3136    62.3 3251.83   65.94 3491.72   62.72 4574.43   62.75
 4599.59   50.02 4600.35   45.98 4607.66   45.98 4608.42   50.09  4642.4    63.2
 5827.01   63.86 5969.06   60.58 6059.07   64.01 6344.09   65.09 7796.22   64.56
 7979.23   69.05 8092.34   65.71 8339.27   67.91 8373.66    61.6 8442.96   69.23
#Mann= 3 , 0 , 0
       0     .15       0 4574.43    .017       0  4642.4     .15       0
#XS Ineff= 2 , 0
       0    4550            4657       0
Permanent Ineff=
       T       T
Bank Sta=4574.43,4642.4
XS Rating Curve= 0
Exp/Cntr=.5,.3

Type RM Length L Ch R = 3 ,17013   ,,,
BEGIN DESCRIPTION:
Riva Ridge Bridge
END DESCRIPTION:
Bridge Culvert--1,0,-1,-1, 0
Deck Dist Width WeirC Skew NumUp NumDn MinLoCord MaxHiCord MaxSubmerge Is_Ogee
5,32,2.6,0, 8, 8, , , .95, 0, 0,0,,
 4570.64 4582.64 4582.64  4606.9 4631.15 4631.15 4640.06  4642.5
   62.97   62.97   62.97   63.06   62.99   62.99   63.02    63.2
     -.2     -.2   60.84   60.93   60.86     -.2     -.2       0
 4567.64 4579.64 4579.64  4603.9 4628.15 4628.15 4637.06  4639.5
   62.97   62.97   62.97   63.06   62.99   62.99   63.02    63.2
     -.2     -.2   60.84   60.93   60.86     -.2     -.2       0
BR Coef=-1 , 0 , 0 ,, 0 ,,,.8,-1,,0,
WSPro=,,,, 1 ,,,, 0 ,,,, 0 ,,,,-1 ,-1 ,-1 , 0 , 0 , 0 , 0 , 0
BC Design=,, 0 ,, 0 ,,,,,,

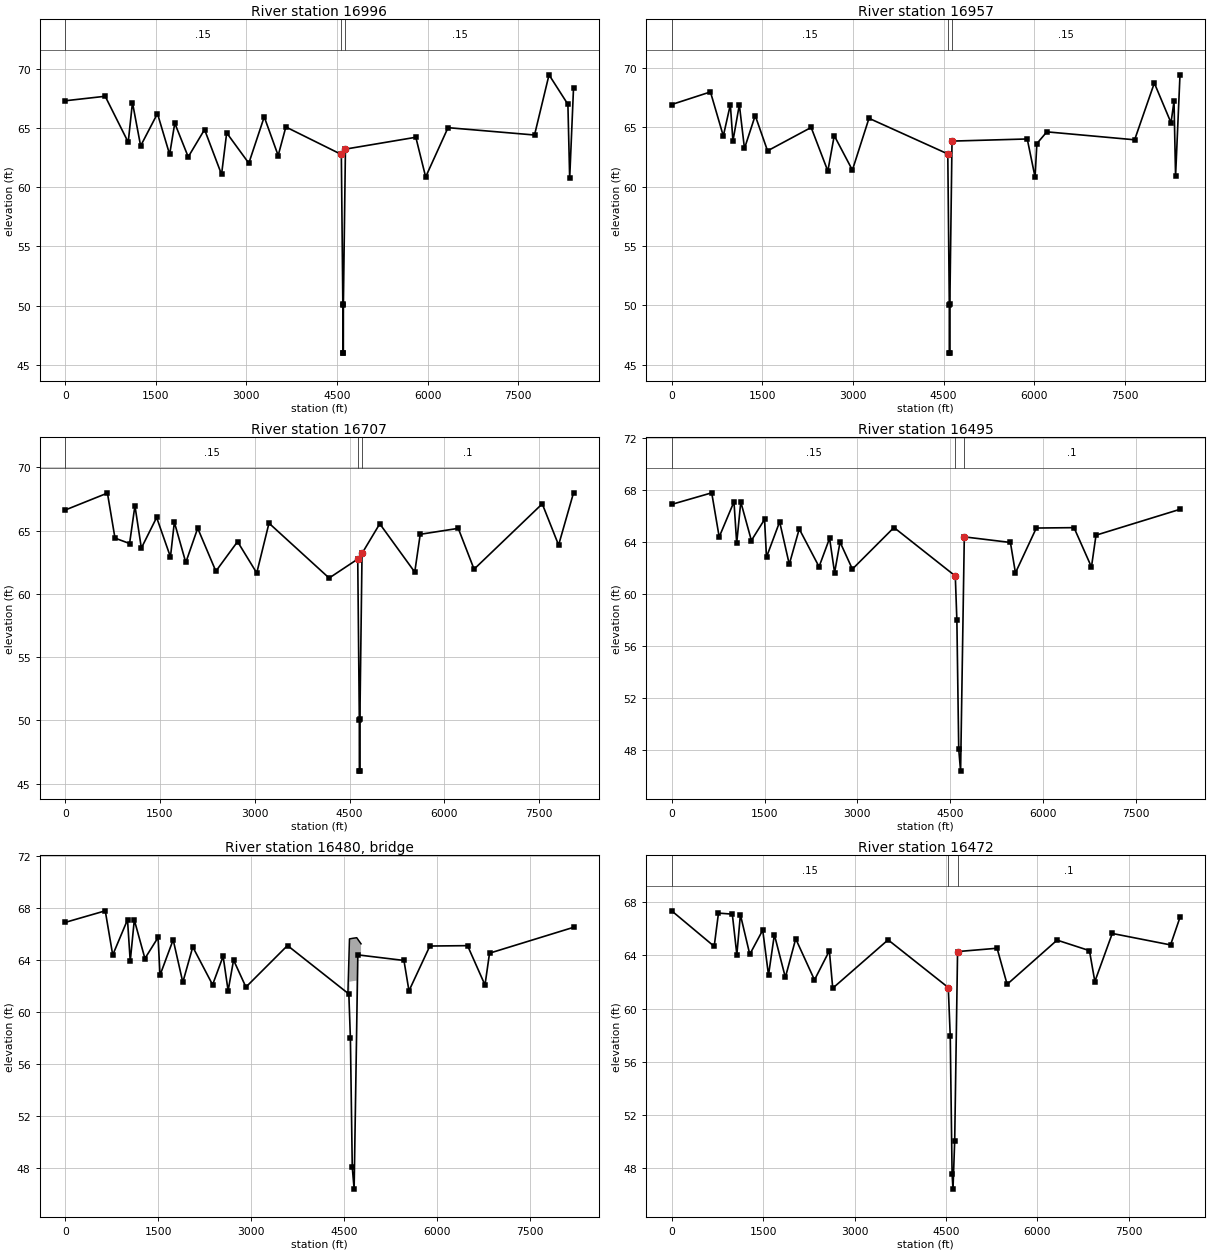
Type RM Length L Ch R = 1 ,16996   ,35.92,38.31,38.29
BEGIN DESCRIPTION:
16995.56  Survey
END DESCRIPTION:
XS GIS Cut Line= 6
     3072371.513    13799650.328     3074433.638    13797717.086
     3074990.183    13796319.377     3075015.986     13796091.79
     3075022.596    13796011.177     3075071.299    13792236.774
#Sta/Elev= 30
       0   67.28  662.09   67.66 1043.11   63.78 1113.43   67.13 1248.72   63.47
 1527.31    66.2 1728.94   62.75 1813.83   65.39 2036.69   62.54 2306.96   64.85
 2588.52   61.06 2673.42   64.57  3039.8   62.01 3295.02   65.92 3525.81   62.66
 3652.99   65.07 4571.43   62.75 4596.59   50.02 4597.35   45.98 4604.66   45.98
 4605.42   50.09  4639.4    63.2 5804.65    64.2 5967.56   60.85 6337.82   65.01
 7769.93   64.39 8009.95   69.47 8322.38   66.98    8352   60.73 8415.71   68.38
#Mann= 3 , 0 , 0
       0     .15       0 4571.43    .017       0  4639.4     .15       0
#XS Ineff= 2 , 0
       0    4549            4656       0
Permanent Ineff=
       T       T
Bank Sta=4571.43,4639.4
XS Rating Curve= 0
Exp/Cntr=.5,.3

Type RM Length L Ch R = 1 ,16957   ,143.51,250.54,361.25
BEGIN DESCRIPTION:
 16957.25
END DESCRIPTION:
XS GIS Cut Line= 6
     3072409.736    13799652.717     3074461.504    13797726.251
     3075023.213    13796319.841     3075054.208     13796094.18
     3075060.818    13796013.566     3075109.522    13792239.164
#Sta/Elev= 30
       0   66.91  641.64   67.97   854.6   64.26  970.85    66.9 1013.77   63.84
 1119.89   66.89 1204.79   63.21 1382.36   65.98 1586.81   63.01 2308.27   64.98
 2584.33   61.31 2690.45   64.29 2990.76   61.39 3265.34   65.75 4569.43   62.75
 4594.59   50.02 4595.35   45.98 4602.62   45.98 4603.42   50.09 4639.43   63.83
 5884.29   64.01 6013.71    60.8 6043.71   63.62 6208.72   64.61 7661.51   63.94
 7987.33   68.72  8263.9   65.37 8313.16   67.21  8338.9   60.87 8412.25   69.41
#Mann= 3 , 0 , 0
       0     .15       0 4569.43    .017       0 4639.43     .15       0
#XS Ineff= 2 , 0
       0    4525            4670       0
Permanent Ineff=
       T       T
Bank Sta=4569.43,4639.43
XS Rating Curve= 0
Exp/Cntr=.3,.1

Type RM Length L Ch R = 1 ,16707   ,128.93,222.21,292.49
BEGIN DESCRIPTION:
 16706.75
END DESCRIPTION:
XS GIS Cut Line= 6
     3072440.912    13799660.242     3074482.196     13797752.42
     3075050.698      13796315.4     3075243.635    13796154.502
     3075833.737    13795599.364     3077331.277    13793422.894
#Sta/Elev= 30
       0   66.63  668.12   67.97  787.53   64.41 1018.34   63.98 1103.24   66.97
 1204.92   63.62 1446.56   66.04 1665.22   62.92 1726.82   65.67 1907.88   62.48
 2096.38   65.19 2383.82   61.79 2726.98   64.13 3030.54   61.65 3224.11   65.59
 4175.85   61.25 4628.43   62.75 4653.59   50.02 4654.35   45.98 4661.66   45.98
 4662.42   50.09  4696.4    63.2 4976.88   65.54 5530.56   61.72 5617.02   64.71
    6219   65.18 6469.13   61.95 7547.75   67.12 7806.53   63.86 8042.75   67.99
#Mann= 3 , 0 , 0
       0     .15       0 4628.43    .017       0  4696.4      .1       0
#XS Ineff= 2 , 0
       0    4605            4729       0
Permanent Ineff=
       T       T
Bank Sta=4628.43,4696.4
XS Rating Curve= 0
Exp/Cntr=.5,.3

Type RM Length L Ch R = 1 ,16495   ,22.43,22.85,47.79
BEGIN DESCRIPTION:
 16494.57
END DESCRIPTION:
XS GIS Cut Line= 6
     3072450.116    13799689.855     3074496.929    13797775.604
     3075069.111    13796340.123     3075461.328    13796292.998
     3075900.306    13795950.878     3077449.011    13793489.119
#Sta/Elev= 30
       0   66.92  646.78   67.81  767.46   64.41 1006.29   67.12 1050.21   63.93
 1116.09   67.11 1287.47   64.14 1499.72   65.76 1531.56   62.86 1743.81   65.58
 1899.58   62.31 2060.37   65.03 2380.56   62.12 2550.36   64.31 2631.33   61.66
 2719.17   64.02 2918.84   61.94  3590.4   65.14 4580.93   61.41 4606.34   57.99
 4636.34   48.08 4666.34   46.39 4726.34   64.42  5471.1   63.99 5552.32   61.65
 5889.54    65.1 6498.33   65.13 6780.03    62.1 6853.38   64.55 8210.11   66.54
#Mann= 3 , 0 , 0
       0     .15       0 4580.93     .04       0 4726.34      .1       0
#XS Ineff= 2 , 0
       0    4548            4779       0
Permanent Ineff=
       T       T
Bank Sta=4580.93,4726.34
XS Rating Curve= 0
Exp/Cntr=.5,.3

Type RM Length L Ch R = 3 ,16480   ,,,
BEGIN DESCRIPTION:
Crosswalk Bridge at Patio Glen
END DESCRIPTION:
Bridge Culvert--1,0,-1,-1, 0
Deck Dist Width WeirC Skew NumUp NumDn MinLoCord MaxHiCord MaxSubmerge Is_Ogee
5,6,2.6,0, 7, 7, , , .95, 0, 0,0,,
 4564.82 4591.22 4591.22 4649.72 4708.22 4708.22    4778
   61.34   65.65   65.65    65.7   65.74   65.74   65.27
       0       0   62.35    62.4   62.44       0       0
 4527.82 4554.22 4554.22 4612.72 4671.22 4671.22    4741
   61.34   65.65   65.65    65.7   65.74   65.74   65.27
       0       0   62.35    62.4   62.44       0       0
BR Coef=-1 , 0 , 0 ,, 0 ,,,.8,-1,,0,
WSPro=,,,, 1 ,,,, 0 ,,,, 0 ,,,,-1 ,-1 ,-1 , 0 , 0 , 0 , 0 , 0
BC Design=,, 0 ,, 0 ,,,,,,

Type RM Length L Ch R = 1 ,16472   ,101.14,103.96,107.1
BEGIN DESCRIPTION:
 16471.72
END DESCRIPTION:
XS GIS Cut Line= 6
     3072482.024    13799697.832     3074515.148    13797794.857
     3075093.049    13796355.616     3075461.971    13796315.849
     3076035.437    13796163.131     3077485.803    13793496.477
#Sta/Elev= 30
       0   67.35  697.45   64.68  767.68   67.18   994.6    67.1 1068.89   64.06
 1127.28   67.06 1280.94   64.08 1493.38    65.9 1588.25   62.52 1684.41   65.56
 1864.82   62.35 2034.61   65.25 2342.37   62.16 2586.46   64.35 2641.88   61.54
 3549.57   65.17 4536.82   61.59 4569.29   57.93  4599.3   47.62  4614.3   46.45
 4642.28   50.09  4689.3   64.29 5337.39   64.54 5502.15   61.83 6321.63   65.15
 6852.58   64.36 6941.06   62.04 7226.74   65.65 8182.94   64.79 8337.78   66.86
#Mann= 3 , 0 , 0
       0     .15       0 4536.82     .04       0  4689.3      .1       0
#XS Ineff= 2 , 0
       0    4420            4741       0
Permanent Ineff=
       T       T
Bank Sta=4536.82,4689.3
XS Rating Curve= 0
Exp/Cntr=.5,.3