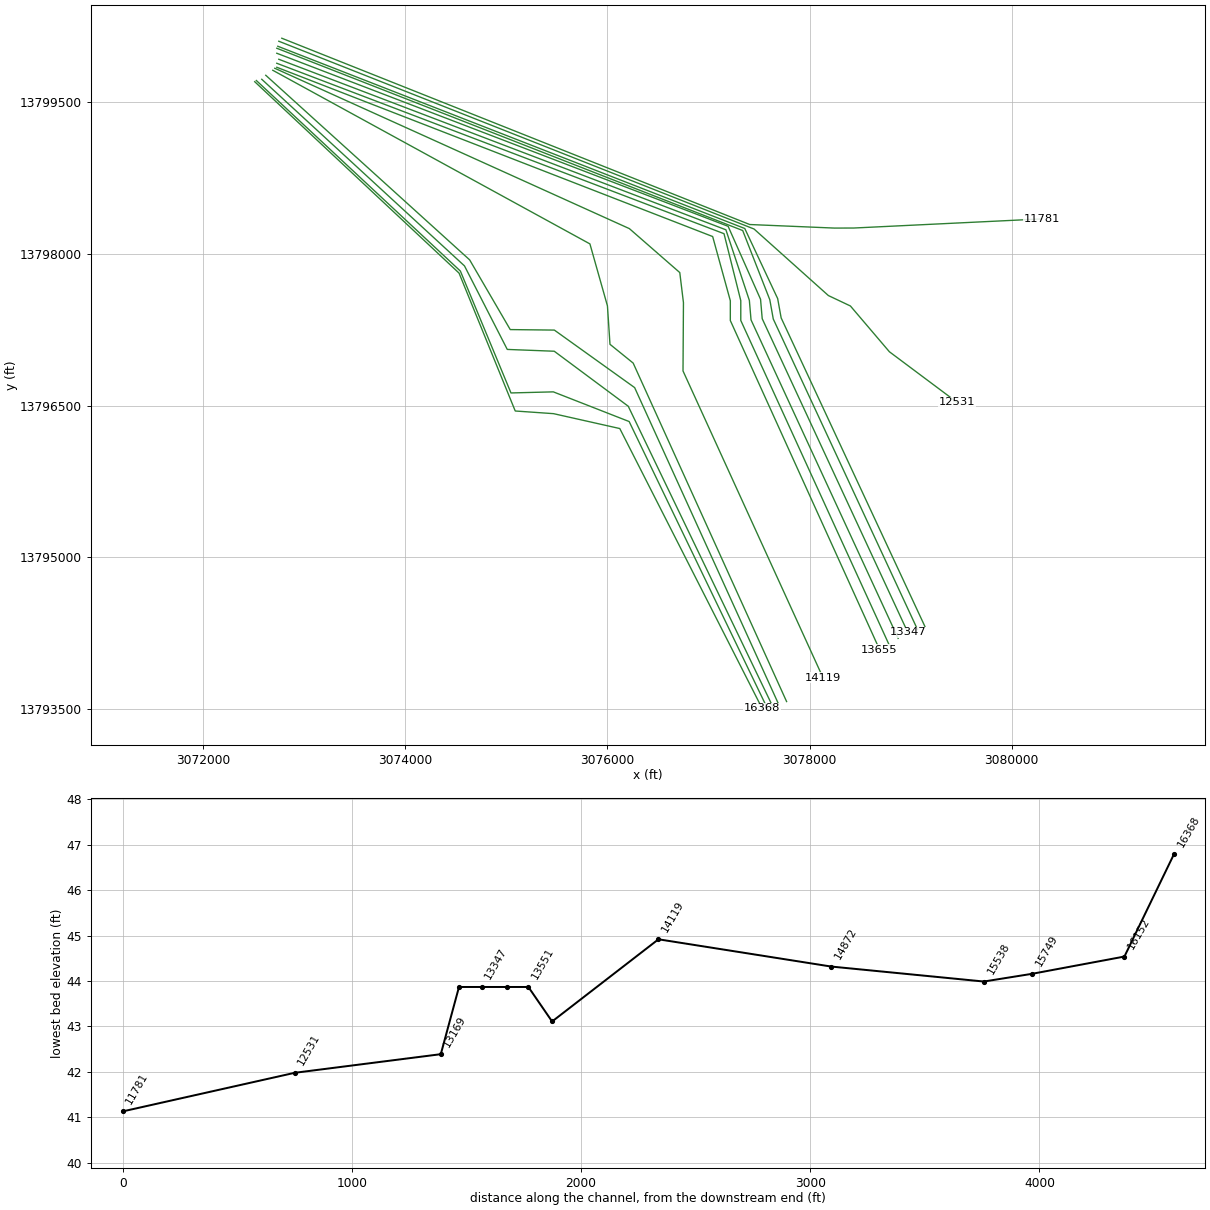
HEC-RAS study D140-00-00.prj: D140-00-00

--- D140-00-00.g02 (geometry) --- (continued)

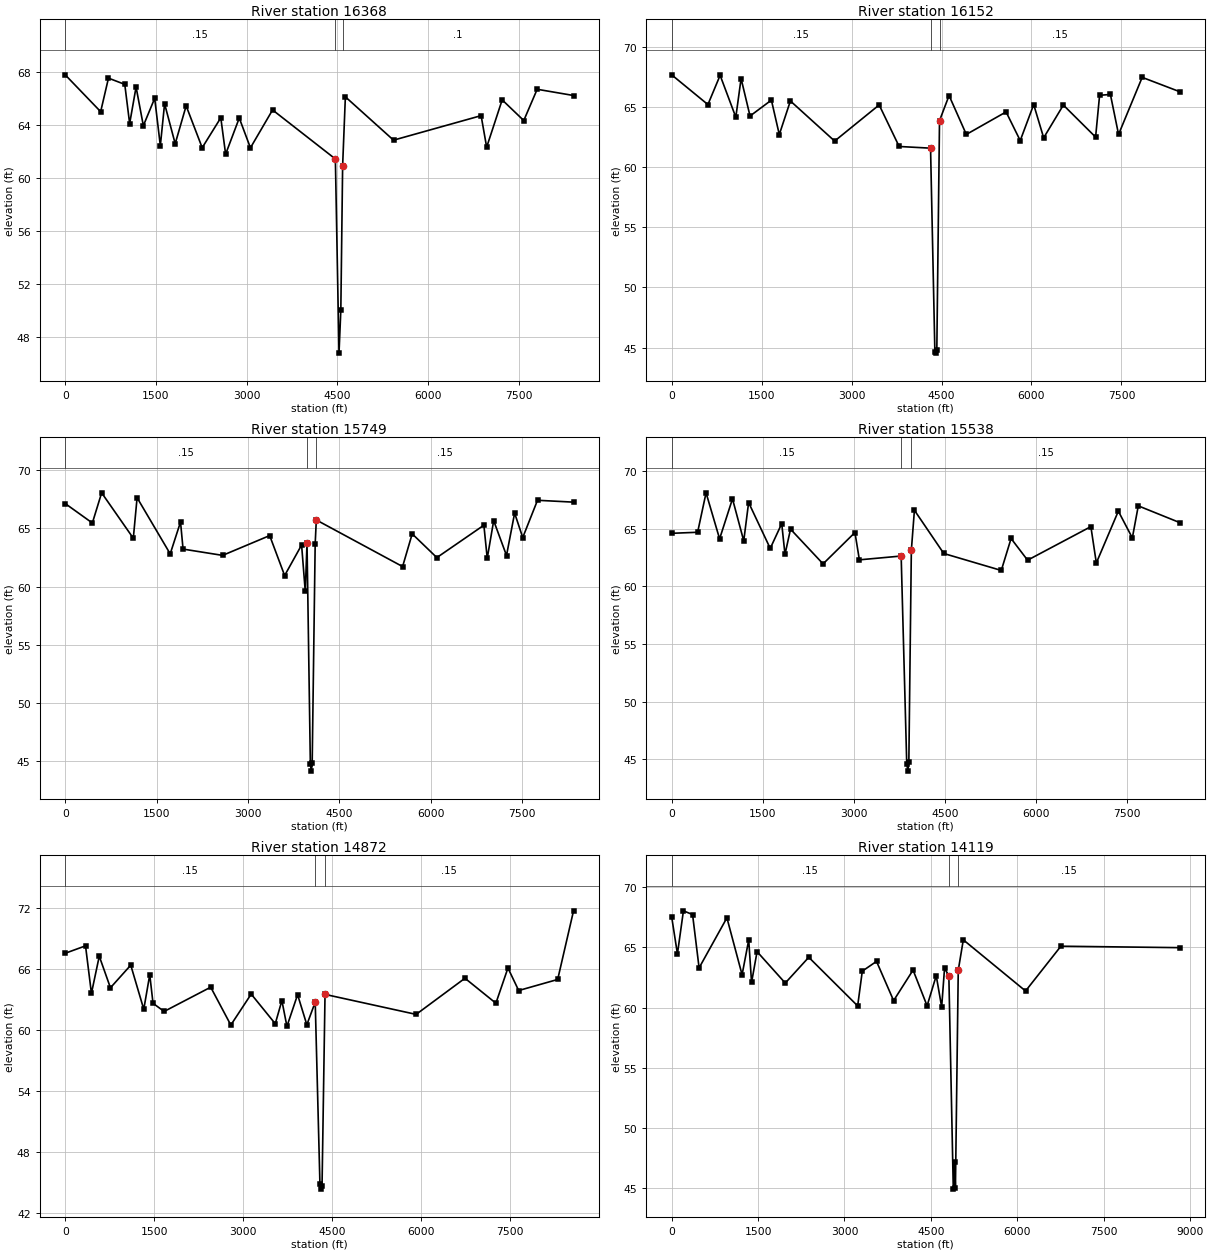
Type RM Length L Ch R = 1 ,16368   ,207.7,215.79,207.82
BEGIN DESCRIPTION:
 16367.72
END DESCRIPTION:
XS GIS Cut Line= 6
     3072509.944    13799705.809     3074531.823    13797811.099
     3075087.746     13796446.13     3075466.641    13796419.831
     3076122.308    13796272.474     3077529.953    13793503.836
#Sta/Elev= 30
       0   67.79  585.95   65.01  715.17   67.54  984.68   67.07 1065.37   64.11
 1171.49   66.87 1291.79   63.95 1479.24   66.02 1572.68   62.44 1642.78   65.61
 1818.27   62.59 1999.24   65.45 2264.55   62.29  2572.3   64.55 2651.86    61.8
 2877.37   64.53 3061.91   62.28 3428.04   65.14 4466.27   61.44 4526.27   46.79
 4556.27   50.01 4586.27   60.94 4631.42   66.13 5427.71   62.86 6875.49   64.71
 6967.18   62.33 7223.76    65.9 7580.74   64.34 7802.21    66.7 8403.37   66.23
#Mann= 3 , 0 , 0
       0     .15       0 4466.27     .04       0 4586.27      .1       0
#XS Ineff= 2 , 0
       0    4420            4657       0
Permanent Ineff=
       T       T
Bank Sta=4466.27,4586.27
XS Rating Curve= 0
Exp/Cntr=.3,.1

Type RM Length L Ch R = 1 ,16152   ,407.69,402.89,386.8
BEGIN DESCRIPTION:
16151.84  Survey
END DESCRIPTION:
XS GIS Cut Line= 6
     3072525.899    13799717.775     3074544.909    13797831.504
     3075045.591    13796624.859     3075464.385    13796635.613
     3076214.922    13796341.743     3077596.178    13793474.402
#Sta/Elev= 30
       0   67.65  604.34   65.18  807.89   67.61 1069.72   64.13 1157.61   67.34
 1306.69   64.23 1662.97   65.55 1794.81   62.69  1979.7   65.48 2717.64   62.15
 3460.29   65.15 3793.42    61.7 4317.17   61.56 4389.29   44.65  4407.5   44.54
  4421.8   44.84 4466.49   63.84 4626.02   65.93 4913.84    62.7 5576.73   64.57
  5812.7   62.19  6037.3   65.18 6203.79   62.42 6531.86   65.14 7069.58   62.48
 7136.18   65.95 7316.56   66.02 7452.52    62.7 7846.55   67.44 8477.14   66.24
#Mann= 3 , 0 , 0
       0     .15       0 4317.17     .04       0 4466.49     .15       0
#XS Ineff= 2 , 0
       0    4250            4511       0
Permanent Ineff=
       T       T
Bank Sta=4317.17,4466.49
XS Rating Curve= 0
Exp/Cntr=.3,.1

Type RM Length L Ch R = 1 ,15749   ,208.91,210.58,190.11
BEGIN DESCRIPTION:
15748.83  Survey
END DESCRIPTION:
XS GIS Cut Line= 6
     3072579.709     13799729.64     3074585.715    13797882.273
      3075008.83    13797055.704     3075473.802    13797037.768
        3076206.    13796493.221     3077640.328    13793511.194
#Sta/Elev= 30
       0   67.13  445.61   65.46  597.96   68.05 1117.68   64.15 1179.71   67.63
 1723.21   62.81 1892.67   65.55 1934.21   63.22 2583.08   62.68 3355.91   64.38
 3601.29   60.95 3879.73   63.57 3939.85   59.58 3968.58   63.72 4023.44   44.75
 4039.51   44.16 4053.43   44.84 4102.51   63.66 4121.17   65.72 5537.34   61.72
 5694.64   64.53  6099.3   62.49 6871.22   65.27 6926.44   62.43 7032.14   65.66
  7242.7   62.67 7375.86   66.31 7509.02   64.21 7751.44   67.41 8342.71   67.25
#Mann= 3 , 0 , 0
       0     .15       0 3968.58     .04       0 4121.17     .15       0
#XS Ineff= 2 , 0
       0    3929            4138       0
Permanent Ineff=
       T       T
Bank Sta=3968.58,4121.17
XS Rating Curve= 0
Exp/Cntr=.3,.1

Type RM Length L Ch R = 1 ,15538   ,859.18,666.3,492.2
BEGIN DESCRIPTION:
15538.25  Survey
END DESCRIPTION:
XS GIS Cut Line= 6
     3072619.365    13799769.296      3074636.72    13797942.134
     3075038.224    13797252.093      3075474.82    13797247.063
     3076269.184    13796677.797     3077691.837    13793547.986
#Sta/Elev= 30
       0   64.61  427.22    64.7  566.33   68.12  789.34   64.13 1001.73    67.6
 1186.94   63.95 1267.22   67.28 1623.27    63.3 1812.58   65.45 1866.12   62.78
 1957.49   64.97  2493.5   61.96 3018.32   64.68 3091.61   62.31 3779.65   62.64
 3871.45   44.64 3890.83   43.99 3906.16    44.8 3947.33   63.13 3997.84   66.61
 4481.59   62.86 5428.73   61.39 5590.06   64.16 5861.93   62.28 6904.09   65.19
 6994.03   62.04 7356.52   66.53  7587.2   64.21 7684.94   66.99 8372.06   65.53
#Mann= 3 , 0 , 0
       0     .15       0 3779.65     .04       0 3947.33     .15       0
#XS Ineff= 2 , 0
       0    3748            4010       0
Permanent Ineff=
       T       T
Bank Sta=3779.65,3947.33
XS Rating Curve= 0
Exp/Cntr=.3,.1

Type RM Length L Ch R = 1 ,14872   ,757.74,753.39,747.96
BEGIN DESCRIPTION:
14871.95  Survey
END DESCRIPTION:
XS GIS Cut Line= 6
     3072688.763    13799818.867     3075826.723     13798100.27
     3076000.135    13797486.578     3076025.171     13797106.42
     3076254.712    13796920.462     3077772.779    13793570.061
#Sta/Elev= 30
       0   67.55  342.64   68.28  442.09    63.6  574.34   67.26  762.46   64.15
 1105.11   66.38 1324.78   62.03 1425.57   65.44 1480.76   62.62 1668.28   61.82
 2453.24   64.21 2792.45   60.48 3135.94   63.53 3541.89   60.61 3653.38   62.89
 3738.62   60.35 3918.36   63.47 4074.24   60.51 4215.48   62.74 4295.14   44.81
 4319.39   44.32 4330.41   44.61  4380.9    63.5 5916.99   61.53 6740.38   65.09
 7261.88   62.63 7464.97    66.1 7646.12   63.88 8303.79   64.97    8571   71.73
#Mann= 3 , 0 , 0
       0     .15       0 4215.48     .04       0  4380.9     .15       0
#XS Ineff= 2 , 0
       0    4170            4421       0
Permanent Ineff=
       T       T
Bank Sta=4215.48,4380.9
XS Rating Curve= 0
Exp/Cntr=.3,.1

Type RM Length L Ch R = 1 ,14119   ,457.83,464.04,480.19
BEGIN DESCRIPTION:
14118.57  Survey
END DESCRIPTION:
XS GIS Cut Line= 6
     3072708.591    13799838.695     3076217.241    13798251.381
     3076715.861    13797816.472     3076752.194     13797518.27
     3076747.839    13796842.664     3078133.338    13793805.528
#Sta/Elev= 30
       0   67.54   99.94   64.46  204.12   68.04  362.81   67.73  476.17    63.3
  959.18   67.46  1222.6   62.73 1337.84   65.62 1387.23   62.09 1482.83   64.65
 1972.44   62.04 2380.52   64.18 3229.63   60.14 3310.03   63.03 3557.15   63.84
 3853.93   60.58  4191.6   63.12  4435.2   60.15 4594.01   62.65 4688.29   60.05
 4738.27   63.27 4813.05   62.65 4890.31   44.92 4912.32   47.16 4927.19   44.98
 4976.46    63.1 5064.09   65.63 6145.23   61.38 6758.37    65.1 8826.91   64.98
#Mann= 3 , 0 , 0
       0     .15       0 4813.05     .04       0 4976.46     .15       0
#XS Ineff= 2 , 0
       0    4770            5030       0
Permanent Ineff=
       T       T
Bank Sta=4813.05,4976.46
XS Rating Curve= 0
Exp/Cntr=.3,.1

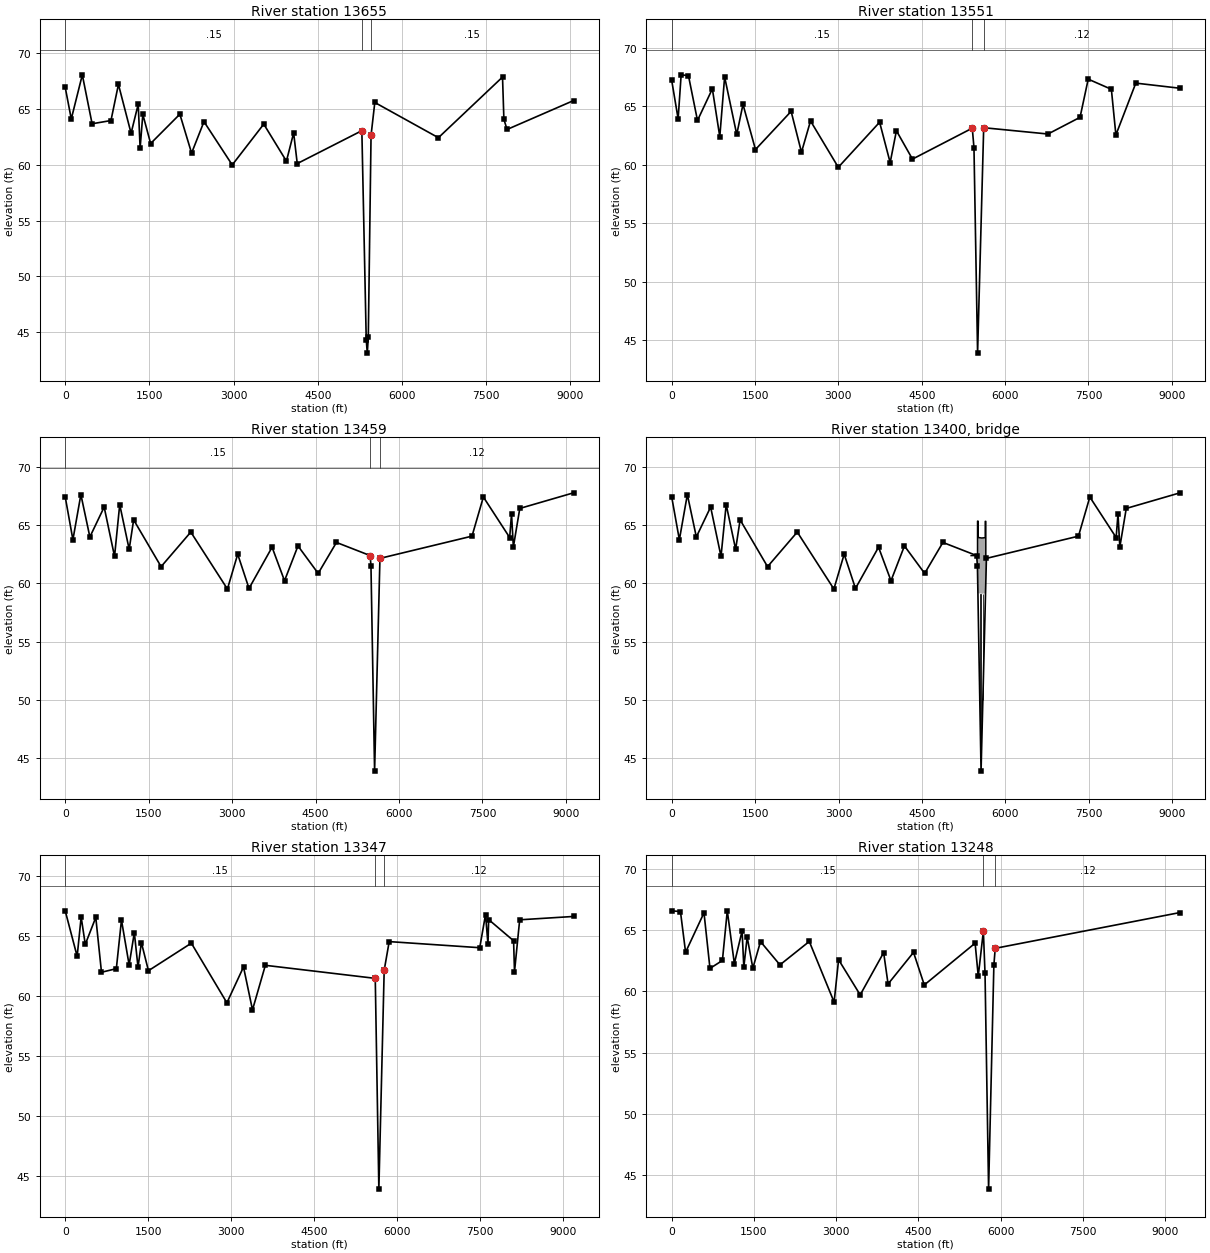
Type RM Length L Ch R = 1 ,13655   ,103.89,103.6,102.2
BEGIN DESCRIPTION:
13654.52  Survey
END DESCRIPTION:
XS GIS Cut Line= 5
     3072728.419    13799848.609      3077041.23    13798173.186
     3077215.952    13797537.825     3077215.952    13797341.664
     3078692.573    13794085.146
#Sta/Elev= 30
       0   66.95  108.32   64.11  304.76   68.07  479.19   63.68  815.29   63.97
  948.45   67.21 1173.74   62.83    1301   65.44 1334.66    61.5 1382.93   64.52
 1522.27   61.91 2042.71   64.54 2251.91   61.05 2472.63   63.87 2976.05   59.99
 3537.88   63.65 3941.58   60.33 4070.32   62.86 4134.68   60.11 5285.76   63.06
 5363.78   44.33 5382.61   43.11 5400.65   44.57 5449.67   62.64 5516.45   65.59
 6649.63   62.43 7792.29   67.87  7816.8   64.07 7873.46   63.17 9057.58   65.76
#Mann= 3 , 0 , 0
       0     .15       0 5285.76     .04       0 5449.67     .15       0
#XS Ineff= 2 , 0
       0    5270            5525       0
Permanent Ineff=
       T       T
Bank Sta=5285.76,5449.67
XS Rating Curve= 0
Exp/Cntr=.3,.1

Type RM Length L Ch R = 1 ,13551   ,80.95,92.39,102.39
BEGIN DESCRIPTION:
 13550.92
END DESCRIPTION:
XS GIS Cut Line= 5
     3072728.419    13799888.265     3077153.574    13798201.232
     3077319.434    13797538.671     3077319.434     13797342.51
     3078788.232    13794129.296
#Sta/Elev= 30
       0   67.25   116.1   63.94  170.58   67.71  302.06   67.64  464.56    63.8
  732.08   66.51  865.88   62.41  952.91   67.53 1170.89    62.6 1283.26   65.18
 1508.01   61.31 2149.65   64.58 2335.96   61.08 2498.67   63.76 2998.42   59.79
 3742.25   63.65 3932.02   60.19 4044.51   62.92 4333.35   60.49 5409.74   63.14
 5440.22   61.47 5505.33   43.87 5615.16   63.18 6771.84   62.64  7349.1   64.07
 7496.25   67.34 7913.01   66.47 7994.28   62.56 8352.47      67    9148   66.56
#Mann= 3 , 0 , 0
       0     .15       0 5409.74     .04       0 5615.16     .12       0
#XS Ineff= 2 , 0
       0    5394            5677       0
Permanent Ineff=
       T       T
Bank Sta=5409.74,5615.16
XS Rating Curve= 0
Exp/Cntr=.5,.3

Type RM Length L Ch R = 1 ,13459   ,108.82,111.35,113.99
BEGIN DESCRIPTION:
 13458.52
END DESCRIPTION:
XS GIS Cut Line= 5
     3072748.248    13799927.921     3077172.125    13798239.905
     3077404.367    13797540.749     3077420.881     13797348.17
     3078876.532    13794195.521
#Sta/Elev= 30
       0   67.43  138.34   63.74  281.69   67.62  443.38   63.98  700.26   66.55
   886.8   62.31  979.76   66.76  1149.8   62.92 1230.07   65.45 1723.49   61.43
 2257.58    64.4 2915.83   59.51 3100.77    62.5 3303.91   59.56 3718.58    63.1
 3942.29   60.22 4184.17   63.21 4547.33   60.85  4875.6   63.51 5482.23   62.38
 5496.22   61.47 5561.33   43.87 5657.56   62.14 7312.39   64.05 7516.62   67.41
 7989.78   63.93 8022.83   65.96 8055.87   63.12 8171.52   66.43 9137.47   67.77
#Mann= 3 , 0 , 0
       0     .15       0 5482.23     .04       0 5657.56     .12       0
#XS Ineff= 2 , 0
       0    5442            5694       0
Permanent Ineff=
       T       T
Bank Sta=5482.23,5657.56
XS Rating Curve= 0
Exp/Cntr=.5,.3

Type RM Length L Ch R = 3 ,13400   ,,,
BEGIN DESCRIPTION:
Fondren Bridge
END DESCRIPTION:
Bridge Culvert--1,0,-1,-1, 0
Deck Dist Width WeirC Skew NumUp NumDn MinLoCord MaxHiCord MaxSubmerge Is_Ogee
5,90,2.6,0, 11, 11, , , .95, 0, 0,0,,
 5383.06 5498.09 5498.09 5508.09 5508.09 5572.18 5636.27 5636.27 5646.92 5646.92
  5668.6
   62.38   62.38   65.34   65.34   63.94   63.89   63.92   65.32   65.32   62.38
   62.14
     -.2     -.2     -.2     -.2   59.15    59.1   59.13     -.2     -.2     -.2
     -.2
    5578 5607.09 5607.09 5617.09 5617.09 5681.18 5745.27 5745.27 5755.92 5755.92
 5777.57
      62   62.14   65.34   65.34   63.94   63.89   63.92   65.32   65.32   62.14
   62.14
     -.2     -.2     -.2     -.2   59.15    59.1   59.13     -.2     -.2     -.2
     -.2
Pier Skew, UpSta & Num, DnSta & Num=  ,5550.82, 2 ,5659.82, 2 , 0 , 0 , 0 ,,
       2       2
       0     100
       2       2
       0     100
Pier Skew, UpSta & Num, DnSta & Num=  ,5593.54, 2 ,5702.54, 2 , 0 , 0 , 0 ,,
       2       2
       0     100
       2       2
       0     100
BR Coef=-1 , 1 , 1 ,1.25, 0 ,,,.8,-1,2,0,
WSPro=,,,, 1 ,,,, 0 ,,,, 0 ,,,,-1 ,-1 ,-1 , 0 , 0 , 0 , 0 , 0
BC Design=,, 0 ,, 0 ,,,,,,

Type RM Length L Ch R = 1 ,13347   ,90.67,98.97,106.2
BEGIN DESCRIPTION:
13347.17  Survey
END DESCRIPTION:
XS GIS Cut Line= 5
     3072728.419    13799987.406     3077194.245    13798274.265
     3077515.019    13797552.179     3077531.533      13797359.6
     3078972.191    13794254.388
#Sta/Elev= 30
       0   67.11  215.96   63.31   288.2   66.59   362.7   64.31   552.7   66.56
  655.86   61.98  924.27   62.28 1017.16   66.34 1155.75   62.59 1249.39   65.29
 1316.41    62.4 1377.11   64.46 1504.84   62.11 2280.36   64.41 2922.99   59.43
 3223.34   62.42 3385.91   58.84 3618.14   62.56 5605.22   61.47 5670.33   43.87
 5766.56   62.14 5857.06   64.54  7494.1   64.03 7598.71    66.8 7642.92   64.32
 7655.19   66.38 8105.93   64.61 8122.46   62.02 8216.23   66.36  9189.7   66.64
#Mann= 3 , 0 , 0
       0     .15       0 5605.22     .04       0 5766.56     .12       0
#XS Ineff= 2 , 0
       0    5557            5782       0
Permanent Ineff=
       T       T
Bank Sta=5605.22,5766.56
XS Rating Curve= 0
Exp/Cntr=.5,.3

Type RM Length L Ch R = 1 ,13248   ,78.16,79.4,81.62
BEGIN DESCRIPTION:
 13248.2
END DESCRIPTION:
XS GIS Cut Line= 5
     3072728.419    13800036.976     3077338.458    13798232.617
     3077606.572    13797547.748     3077640.981     13797356.67
     3079067.849    13794283.822
#Sta/Elev= 30
       0   66.58  160.09   66.52  253.58    63.2  589.31   66.42   698.2   61.88
  925.04   62.53 1013.82   66.58 1142.68   62.28 1283.92   64.94 1315.53   61.98
 1376.53   64.44 1480.15    61.9 1619.65   64.07 1974.01   62.17 2509.02   64.08
 2961.73   59.13 3043.43   62.59 3437.21   59.72 3864.94   63.17 3945.48   60.61
 4409.67   63.19 4605.91   60.53 5532.61   63.94 5589.67   61.25  5683.1   64.92
 5713.22   61.47 5778.33   43.87 5874.56   62.14 5898.92   63.52 9268.17   66.44
#Mann= 3 , 0 , 0
       0     .15       0  5683.1     .04       0 5898.92     .12       0
#XS Ineff= 2 , 0
       0    5667            5987       0
Permanent Ineff=
       T       T
Bank Sta=5683.1,5898.92
XS Rating Curve= 0
Exp/Cntr=.3,.1

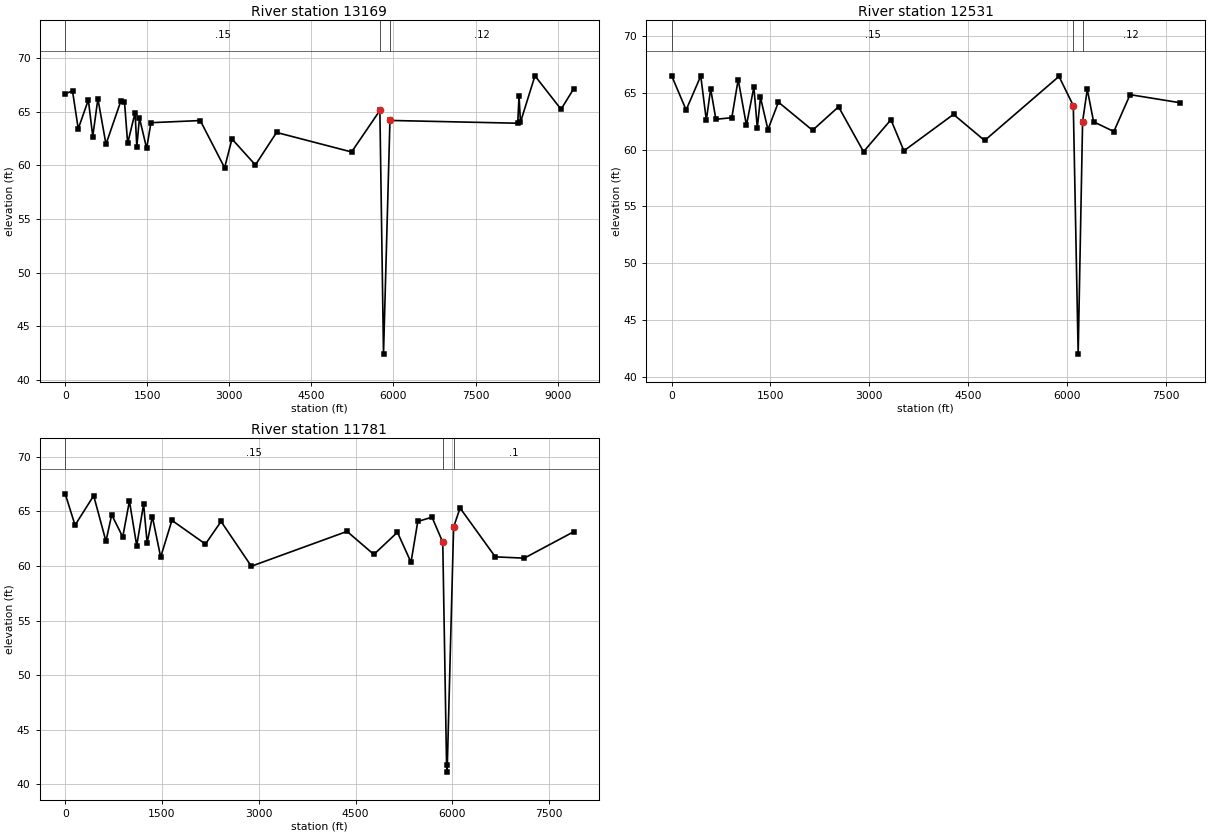
Type RM Length L Ch R = 1 ,13169   ,490.92,637.43,748.73
BEGIN DESCRIPTION:
13168.80  Survey
END DESCRIPTION:
XS GIS Cut Line= 5
     3072738.333    13800056.804     3077358.921    13798252.743
     3077684.464    13797558.805     3077718.873    13797367.727
     3079141.433    13794313.255
#Sta/Elev= 30
       0   66.66   133.3   66.94  238.16    63.4  423.15   66.09  503.66   62.68
  597.17   66.21   745.2   61.96 1018.95   66.02 1083.36   65.94 1141.49   62.04
 1276.59   64.91  1308.8   61.74 1357.11   64.41 1488.92   61.57 1566.44   63.97
  2468.2   64.17 2913.39   59.77  3047.9   62.45 3476.22   60.03 3863.04   63.06
 5233.83   61.24 5751.04   65.11 5817.42   42.39 5935.14   64.18 8270.87   63.92
 8294.59   66.49 8320.52   64.01 8585.27   68.34 9062.27   65.22 9290.45   67.11
#Mann= 3 , 0 , 0
       0     .15       0 5751.04     .04       0 5935.14     .12       0
#XS Ineff= 2 , 0
       0    5722            5987       0
Permanent Ineff=
       T       T
Bank Sta=5751.04,5935.14
XS Rating Curve= 0
Exp/Cntr=.3,.1

Type RM Length L Ch R = 1 ,12531   ,689.44,750.52,832.12
BEGIN DESCRIPTION:
12531.37  Survey
END DESCRIPTION:
XS GIS Cut Line= 6
     3072748.248    13800106.374     3077450.926    13798247.473
     3078186.201    13797588.951     3078404.246    13797485.668
     3078790.015    13797032.494     3079461.576    13796530.453
#Sta/Elev= 30
       0   66.51  219.63    63.5  441.69    66.5  526.09    62.6  591.96   65.36
  671.25   62.68  913.19   62.82 1009.97   66.18 1135.28   62.15 1248.27   65.52
  1300.3   61.92 1348.69    64.6 1461.59   61.77  1620.8   64.19 2139.02   61.71
 2534.03   63.78 2913.23   59.82 3329.29   62.64 3526.15    59.9 4279.57   63.11
 4751.98   60.81  5881.1   66.46 6098.54   63.88 6172.48   41.98 6239.68   62.48
 6310.91   65.32 6406.68   62.46 6714.34    61.6 6960.57   64.85 7718.68   64.14
#Mann= 3 , 0 , 0
       0     .15       0 6098.54     .04       0 6239.68     .12       0
#XS Ineff= 2 , 0
       0    6030            6376       0
Permanent Ineff=
       T       T
Bank Sta=6098.54,6239.68
XS Rating Curve= 0
Exp/Cntr=.3,.1

Type RM Length L Ch R = 1 ,11781   ,79.04,80.48,80.31
BEGIN DESCRIPTION:
11780.85  Survey
END DESCRIPTION:
XS GIS Cut Line= 5
      3072777.99    13800136.117     3077407.856    13798292.101
      3078244.63    13798256.908     3078436.886    13798257.333
     3080298.627    13798347.574
#Sta/Elev= 30
       0   66.61  152.52   63.74  441.19   66.44  631.36   62.27  720.66   64.69
  891.52   62.66  995.14   65.95 1108.16   61.86 1214.84   65.67 1269.62   62.11
 1350.35   64.52 1479.52   60.82 1653.62   64.18 2173.24   62.01 2415.06   64.08
 2884.22   59.98 4367.16   63.17 4782.85   61.06 5148.37   63.09 5358.56   60.34
 5463.65   64.08 5684.01   64.47 5850.75   62.18 5909.48   41.81 5918.63   41.13
 6018.97   63.57 6119.04   65.31 6664.73   60.84 7113.34   60.72 7877.28   63.13
#Mann= 3 , 0 , 0
       0     .15       0 5850.75     .04       0 6018.97      .1       0
#XS Ineff= 2 , 0
       0    5740            6281       0
Permanent Ineff=
       T       T
Bank Sta=5850.75,6018.97
XS Rating Curve= 0
Exp/Cntr=.5,.3