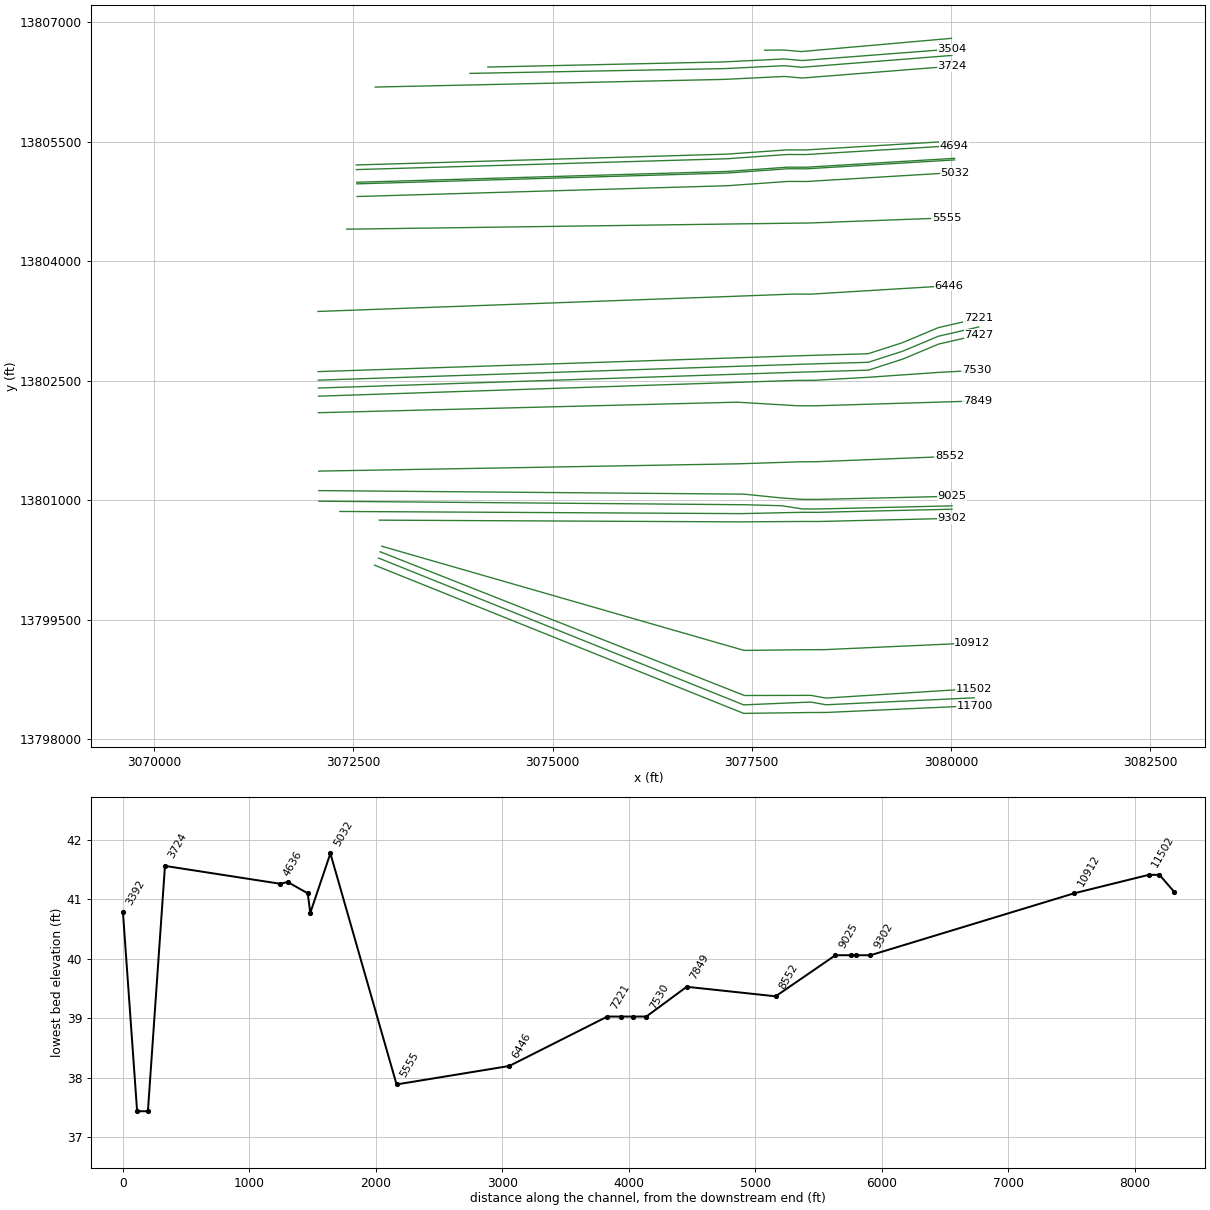
HEC-RAS study D140-00-00.prj: D140-00-00

--- D140-00-00.g02 (geometry) --- (continued)

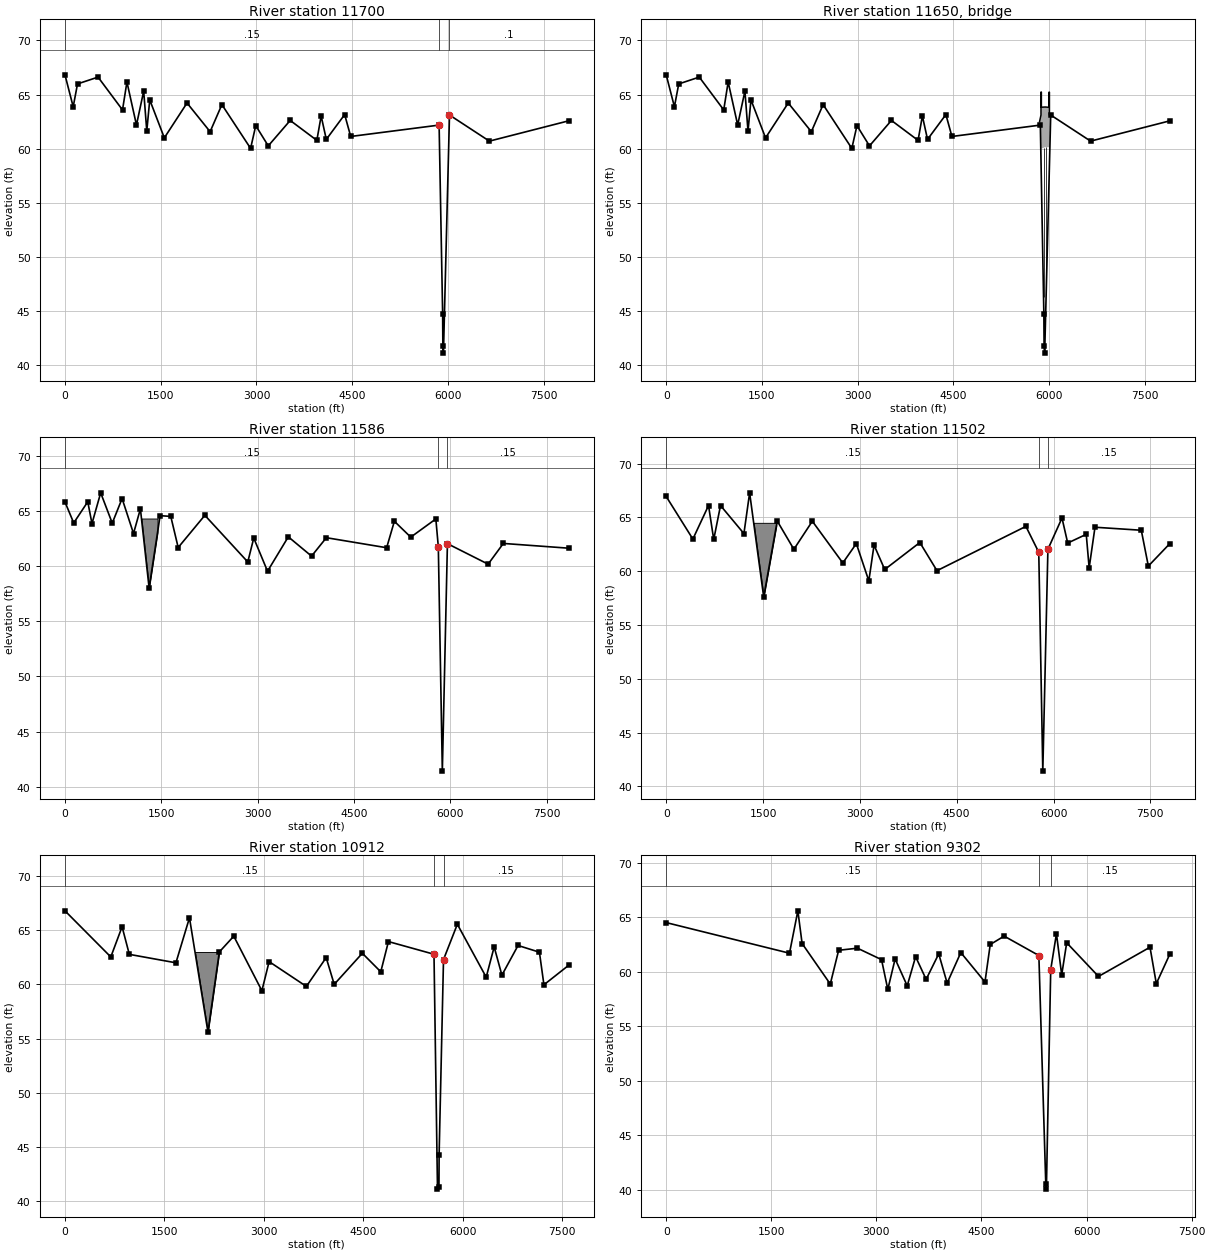
Type RM Length L Ch R = 1 ,11700   ,130.29,114.17,96.52
BEGIN DESCRIPTION:
 11700.37
END DESCRIPTION:
XS GIS Cut Line= 5
     3072768.076    13800185.687     3077397.748    13798326.267
     3078240.678     13798337.29     3078432.934    13798337.715
     3080296.017    13798421.618
#Sta/Elev= 30
       0   66.82  128.87   63.87  196.37   65.98  518.35   66.61  901.56   63.58
  970.75   66.16 1120.12   62.19 1233.28   65.32 1281.77   61.63 1328.27   64.51
 1556.57      61 1912.19   64.22 2273.95   61.57 2458.47   64.07 2908.25   60.03
 2988.98   62.13 3185.03   60.26 3528.65   62.61 3946.19   60.77 4013.59   63.02
 4094.41   60.86  4382.1   63.15 4476.69   61.13 5861.75   62.18 5917.03   44.74
 5920.48   41.81 5929.63   41.13 6024.35   63.11 6649.58    60.7 7889.35   62.57
#Mann= 3 , 0 , 0
       0     .15       0 5861.75     .04       0 6024.35      .1       0
#XS Ineff= 2 , 0
       0    5833            6230       0
Permanent Ineff=
       T       T
Bank Sta=5861.75,6024.35
XS Rating Curve= 0
Exp/Cntr=.5,.3

Type RM Length L Ch R = 3 ,11650   ,,,
BEGIN DESCRIPTION:
Airport Bridge
END DESCRIPTION:
Bridge Culvert--1,0,-1,-1, 0
Deck Dist Width WeirC Skew NumUp NumDn MinLoCord MaxHiCord MaxSubmerge Is_Ogee
5,90,2.6,0, 11, 11, , , .95, 0, 0,0,,
 5848.77 5871.84 5871.84 5878.09 5878.09 5938.09 5998.09 5998.09 6004.34 6004.34
 6024.37
   62.48   63.11   65.23   65.23   63.83   63.85   63.82   65.22   65.22   63.11
   63.11
     -.2     -.2     -.2     -.2   60.01   60.14   60.14     -.2     -.2     -.2
     -.2
    5800 5814.57 5814.57 5820.82 5820.82 5880.82 5940.82 5940.82 5947.07 5947.07
 5952.37
      62   62.04   65.23   65.23   63.83   63.85   63.82   65.22   65.22   62.04
   62.04
     -.2     -.2     -.2     -.2   60.01   60.14   60.14     -.2     -.2     -.2
     -.2
Pier Skew, UpSta & Num, DnSta & Num=  ,5912.09, 2 ,5855.82, 2 , 0 , 0 , 0 ,,
     1.3     1.3
       0     100
     1.3     1.3
       0     100
Pier Skew, UpSta & Num, DnSta & Num=  ,5952.81, 2 ,5896.54, 2 , 0 , 0 , 0 ,,
     1.3     1.3
       0     100
     1.3     1.3
       0     100
BR Coef=-1 , 1 , 1 ,1.25, 0 ,,,.8,-1,2,0,
WSPro=,,,, 1 ,,,, 0 ,,,, 0 ,,,,-1 ,-1 ,-1 , 0 , 0 , 0 , 0 , 0
BC Design=,, 0 ,, 0 ,,,,,,

Type RM Length L Ch R = 1 ,11586   ,85.1,84.6,84.51
BEGIN DESCRIPTION:
11586.20  Survey
END DESCRIPTION:
XS GIS Cut Line= 5
     3072817.646    13800274.913     3077397.879    13798432.991
     3078240.603    13798468.393     3078431.112    13798434.168
     3080292.494    13798521.535
#Sta/Elev= 30
       0   65.82  136.27   63.92  354.89   65.84   420.2   63.86  555.91   66.65
  735.85    63.9  889.05   66.13  1066.9   62.96 1174.01    65.2 1309.41   58.03
 1480.58   64.58 1646.76   64.51    1762   61.69 2177.17   64.61 2845.32   60.38
 2938.18   62.55  3152.5   59.54 3475.85   62.66 3837.56   60.91 4068.17   62.58
  5006.4   61.67 5126.51   64.07 5381.73   62.63 5772.07   64.28 5810.64   61.76
 5873.16   41.41 5952.35   62.04  6585.8   60.18 6822.53   62.06 7837.17   61.63
#Mann= 3 , 0 , 0
       0     .15       0 5810.64     .04       0 5952.35     .15       0
#XS Ineff= 2 , 0
       0    5794            6083       0
Permanent Ineff=
       T       T
#Block Obstruct= 1 ,-1
 1162.39 1440.54   64.32
Bank Sta=5810.64,5952.35
XS Rating Curve= 0
Exp/Cntr=.5,.3

Type RM Length L Ch R = 1 ,11502   ,573.16,589.82,607.31
BEGIN DESCRIPTION:
 11501.6
END DESCRIPTION:
XS GIS Cut Line= 5
     3072837.474    13800354.226     3077407.854    13798550.626
     3078240.601     13798552.29      3078431.11    13798518.066
     3080288.441    13798636.487
#Sta/Elev= 30
       0   66.95  413.33   62.99  655.81   66.11  736.44   62.95  841.58   66.11
 1204.08    63.5 1292.53   67.29 1510.47   57.61 1720.11   64.67 1978.12   62.04
  2263.8   64.65 2736.03   60.77 2945.67   62.57 3139.17    59.1  3219.8   62.43
 3385.39   60.16 3929.33   62.67 4194.78   60.05 5572.48   64.17 5771.64   61.76
 5834.16   41.41 5913.35   62.04 6131.47   64.95 6220.06   62.62 6507.23   63.43
 6552.32   60.31 6642.51   64.09 7359.89   63.81 7469.18   60.48 7800.79   62.56
#Mann= 3 , 0 , 0
       0     .15       0 5771.64     .04       0 5913.35     .15       0
#XS Ineff= 2 , 0
       0    5745            5978       0
Permanent Ineff=
       T       T
#Block Obstruct= 1 ,-1
 1321.15 1706.21    64.5
Bank Sta=5771.64,5913.35
XS Rating Curve= 0
Exp/Cntr=.3,.1

Type RM Length L Ch R = 1 ,10912   ,1610.14,1609.97,1608.84
BEGIN DESCRIPTION:
10911.78  Survey
END DESCRIPTION:
XS GIS Cut Line= 5
     3072857.302    13800423.624     3077403.332    13799116.406
     3078209.887    13799125.263     3078404.145    13799125.569
      3080268.25    13799209.154
#Sta/Elev= 30
       0    66.8  691.59   62.54  861.74   65.33  970.84   62.78 1673.92      62
 1878.35   66.16 2157.11   55.61 2328.51      63 2546.71   64.46  2970.9   59.42
 3079.84   62.11 3642.03   59.82 3940.75   62.48 4061.97   60.01 4486.24   62.88
 4764.41   61.17 4879.97   63.96 5567.36   62.79 5620.21    41.1 5642.32   41.31
 5644.62   44.29 5710.96    62.3 5919.65   65.56 6355.08   60.67 6475.21   63.47
 6591.95   60.86 6835.57    63.6 7157.87   62.98 7225.96   59.97 7597.08   61.76
#Mann= 3 , 0 , 0
       0     .15       0 5567.36     .04       0 5710.96     .15       0
#XS Ineff= 2 , 0
       0    5520            5753       0
Permanent Ineff=
       T       T
#Block Obstruct= 1 ,-1
 1948.54  2331.9      63
Bank Sta=5567.36,5710.96
XS Rating Curve= 0
Exp/Cntr=.3,.1

Type RM Length L Ch R = 1 ,9302    ,114.87,115.09,115
BEGIN DESCRIPTION:
 9301.808
END DESCRIPTION:
XS GIS Cut Line= 5
      3072827.56    13800750.788     3077328.443    13800729.187
     3078140.407      13800734.2     3078336.961    13800733.984
     3080014.264     13800773.14
#Sta/Elev= 30
       0   64.52  1759.8   61.71 1879.23    65.6 1939.96    62.6 2342.02   58.88
 2461.44   61.98 2730.16   62.17 3073.51   61.12 3163.08   58.39 3267.58   61.19
 3439.98   58.72 3559.98   61.39 3709.98   59.31 3889.99   61.65 4009.99   58.97
 4204.99   61.77 4549.99   59.07    4625   62.51 4823.68   63.28 5319.12    61.5
 5419.94   40.06 5427.81   40.49 5488.38   60.21 5570.02    63.5 5645.04   59.72
 5716.38   62.67 6170.19   59.58 6905.39   62.26 6995.41   58.92 7187.23   61.61
#Mann= 3 , 0 , 0
       0     .15       0 5319.12     .04       0 5488.38     .15       0
#XS Ineff= 2 , 0
       0    5300            5548       0
Permanent Ineff=
       T       T
Bank Sta=5319.12,5488.38
XS Rating Curve= 0
Exp/Cntr=.5,.3

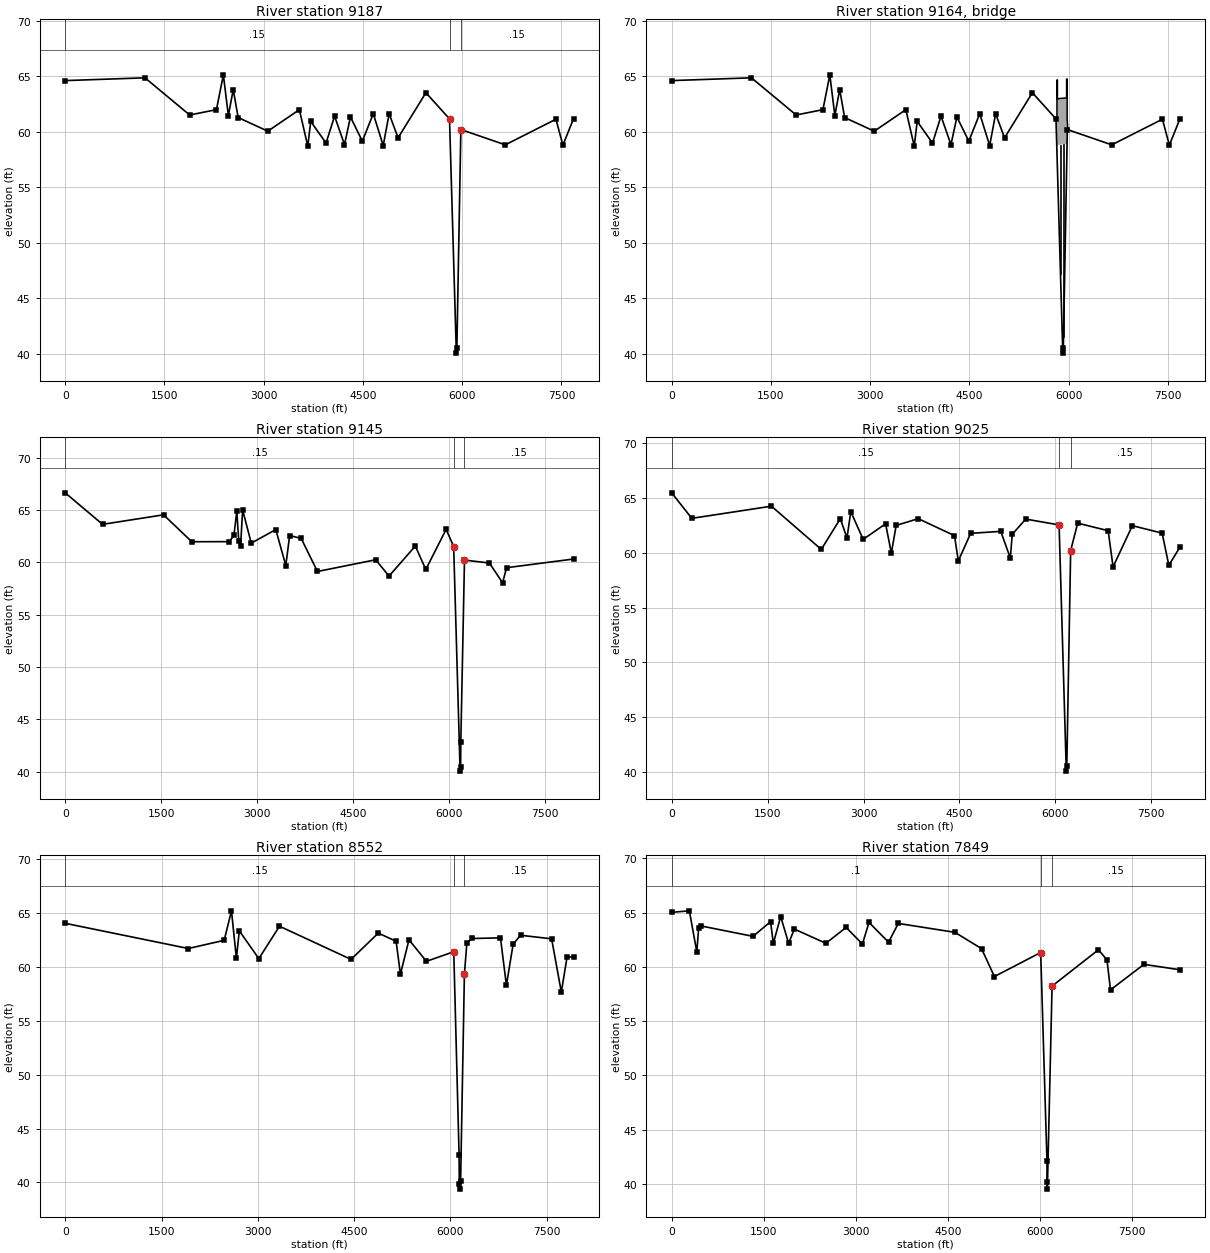
Type RM Length L Ch R = 1 ,9187    ,44.35,42,41.96
BEGIN DESCRIPTION:
 9186.714
END DESCRIPTION:
XS GIS Cut Line= 5
     3072331.857    13800859.843      3077355.43    13800832.686
     3078139.416      13800849.2      3078335.97    13800848.984
     3080013.273     13800888.14
#Sta/Elev= 30
       0   64.62 1205.66   64.87 1880.67   61.52 2285.66      62  2390.1   65.14
 2465.68   61.47  2539.3   63.81 2613.89   61.29 3061.48   60.06 3538.91      62
  3665.7   58.71  3710.7   60.94 3941.73   58.99  4070.7   61.42  4220.7   58.85
 4310.71   61.34 4490.71   59.16 4655.71   61.64 4805.71   58.76 4895.71   61.63
 5030.72   59.46 5450.81   63.53 5807.81   61.17 5910.94   40.06 5918.81   40.49
 5979.38   60.21 6651.07   58.83 7416.28   61.14 7521.31    58.8 7682.12   61.19
#Mann= 3 , 0 , 0
       0     .15       0 5807.81     .04       0 5979.38     .15       0
#XS Ineff= 2 , 0
       0    5800            6037       0
Permanent Ineff=
       T       T
Bank Sta=5807.81,5979.38
XS Rating Curve= 0
Exp/Cntr=.5,.3

Type RM Length L Ch R = 3 ,9164    ,,,
BEGIN DESCRIPTION:
Ludington Bridge
END DESCRIPTION:
Bridge Culvert--1,0,-1,-1, 0
Deck Dist Width WeirC Skew NumUp NumDn MinLoCord MaxHiCord MaxSubmerge Is_Ogee
5,36,2.6,0, 12, 12, , , .95, 0, 0,0,,
 5797.86 5813.99 5822.49 5822.49 5829.99 5829.99 5898.97 5967.94 5967.94 5976.44
 5976.44 5987.39
   61.17   61.17   61.17   64.68   64.68   62.98   63.03   63.06   64.76   64.76
   61.17    60.2
     -.2     -.2     -.2     -.2     -.2   58.82   58.87    58.9     -.2     -.2
     -.2     -.2
    6064 6079.24 6087.74 6087.74 6095.24 6095.24 6164.22 6233.19 6233.19 6240.69
 6240.69 6251.38
   61.05   61.05   61.05   64.68   64.68   62.98   63.03   63.06   64.76   64.76
   61.05   60.21
     -.2     -.2     -.2     -.2     -.2   58.82   58.87    58.9     -.2     -.2
     -.2     -.2
Pier Skew, UpSta & Num, DnSta & Num=  ,5875.97, 2 ,6141.22, 2 , 0 , 0 , 0 ,,
     1.3     1.3
       0     100
     1.3     1.3
       0     100
Pier Skew, UpSta & Num, DnSta & Num=  ,5921.96, 2 ,6187.21, 2 , 0 , 0 , 0 ,,
     1.3     1.3
       0     100
     1.3     1.3
       0     100
BR Coef=-1 , 1 , 1 ,1.25, 0 ,,,.8,-1,2,0,
WSPro=,,,, 1 ,,,, 0 ,,,, 0 ,,,,-1 ,-1 ,-1 , 0 , 0 , 0 , 0 , 0
BC Design=,, 0 ,, 0 ,,,,,,

Type RM Length L Ch R = 1 ,9145    ,119.15,120.14,120.03
BEGIN DESCRIPTION:
9144.717  Survey
END DESCRIPTION:
XS GIS Cut Line= 6
     3072068.368    13800988.687     3077418.292    13800944.053
     3077872.196     13800931.86     3078139.054    13800891.163
     3078335.608    13800890.947      3080012.91    13800930.103
#Sta/Elev= 30
       0   66.63  584.15   63.62 1537.55   64.53  1979.2   61.96 2564.02   61.97
  2638.4   62.56 2683.03   64.87 2714.23   61.99 2742.53   61.58 2774.23   64.99
 2909.23   61.83 3292.96   63.12 3449.25   59.69 3509.25   62.55 3689.26   62.28
 3944.27   59.12 4854.99   60.24 5063.25   58.68 5474.36   61.55 5638.24   59.31
 5956.22   63.14 6074.12    61.5 6174.94   40.06 6182.81   40.49  6185.8   42.84
 6243.38   60.21 6632.66   59.93 6839.44   58.04 6900.89   59.48 7948.43   60.31
#Mann= 3 , 0 , 0
       0     .15       0 6074.12     .04       0 6243.38     .15       0
#XS Ineff= 2 , 0
       0    6070            6301       0
Permanent Ineff=
       T       T
Bank Sta=6074.12,6243.38
XS Rating Curve= 0
Exp/Cntr=.5,.3

Type RM Length L Ch R = 1 ,9025    ,470.66,472.82,474.3
BEGIN DESCRIPTION:
 9024.582
END DESCRIPTION:
XS GIS Cut Line= 6
      3072067.77    13801121.457     3077403.145     13801077.06
     3077886.214     13801027.99     3078138.019      13801011.2
     3078334.573    13801010.984     3080011.876     13801050.14
#Sta/Elev= 30
       0   65.48  314.74   63.15 1559.78   64.26  2339.3   60.31 2636.84   63.12
 2740.97   61.35 2800.48   63.76 2993.88   61.23 3344.85   62.65 3434.85   59.97
 3509.85    62.5 3854.86   63.12 4422.04   61.57 4481.55   59.26 4674.95   61.78
 5144.91   61.96 5294.91   59.53 5324.91   61.69 5535.31   63.08 6057.43   62.55
 6169.94   40.06 6177.81   40.49 6238.38   60.21 6348.29   62.71 6824.54   62.02
 6901.35   58.72 7203.21   62.48 7668.34    61.8 7773.37   58.86 7947.79   60.53
#Mann= 3 , 0 , 0
       0     .15       0 6057.43     .04       0 6238.38     .15       0
#XS Ineff= 2 , 0
       0    5980            6320       0
Permanent Ineff=
       T       T
Bank Sta=6057.43,6238.38
XS Rating Curve= 0
Exp/Cntr=.3,.1

Type RM Length L Ch R = 1 ,8552    ,704.2,702.96,701.36
BEGIN DESCRIPTION:
8551.761  Survey
END DESCRIPTION:
XS GIS Cut Line= 5
     3072066.667    13801366.129     3077329.311    13801457.792
     3078118.058    13801483.123     3078310.934       13801484.
     3079982.532    13801550.055
#Sta/Elev= 30
       0   64.06 1918.16   61.72 2476.21   62.48 2589.96   65.22  2666.3   60.82
  2712.1   63.36 3016.29   60.78  3338.1   63.79 4452.68   60.71 4876.57   63.15
 5155.02   62.39 5221.62   59.33 5354.91   62.53 5626.82   60.53 6052.59   61.42
 6135.63   42.55 6139.14    39.8 6149.57   39.37 6159.25   40.08 6218.37   59.32
 6257.05   62.26 6342.44   62.65 6780.06   62.71 6872.53   58.31 6977.61   62.12
 7092.65   62.95 7577.16   62.62  7728.2   57.67 7818.27   60.95 7918.38   60.91
#Mann= 3 , 0 , 0
       0     .15       0 6052.59     .04       0 6218.37     .15       0
#XS Ineff= 2 , 0
       0    5980            6286       0
Permanent Ineff=
       T       T
Bank Sta=6052.59,6218.37
XS Rating Curve= 0
Exp/Cntr=.3,.1

Type RM Length L Ch R = 1 ,7849    ,318.4,319.24,320.55
BEGIN DESCRIPTION:
7848.797  Survey
END DESCRIPTION:
XS GIS Cut Line= 5
     3072063.365    13802098.973     3077315.205    13802231.011
     3078073.695    13802186.102     3078301.744     13802185.57
     3080334.239    13802246.267
#Sta/Elev= 30
       0   65.02  287.94   65.16  409.26   61.37  439.27    63.6  484.29   63.76
 1324.55   62.81 1609.64   64.16 1654.66   62.17  1774.7   64.63 1904.07   62.16
 1996.42   63.48 2509.93   62.17 2840.03   63.63 3104.62    62.1 3212.36   64.09
 3530.25   62.27  3689.5      64 4610.59   63.18 5043.97   61.68  5253.5   59.11
 6007.11   61.32 6109.11   42.12 6111.05   40.22 6115.87   39.53 6192.22   58.23
 6946.55   61.57 7085.77   60.65 7143.55   57.88 7687.77   60.23 8274.77   59.73
#Mann= 3 , 0 , 0
       0      .1       0 6007.11     .04       0 6192.22     .15       0
#XS Ineff= 2 , 0
       0    5945            6293       0
Permanent Ineff=
       T       T
Bank Sta=6007.11,6192.22
XS Rating Curve= 0
Exp/Cntr=.3,.1

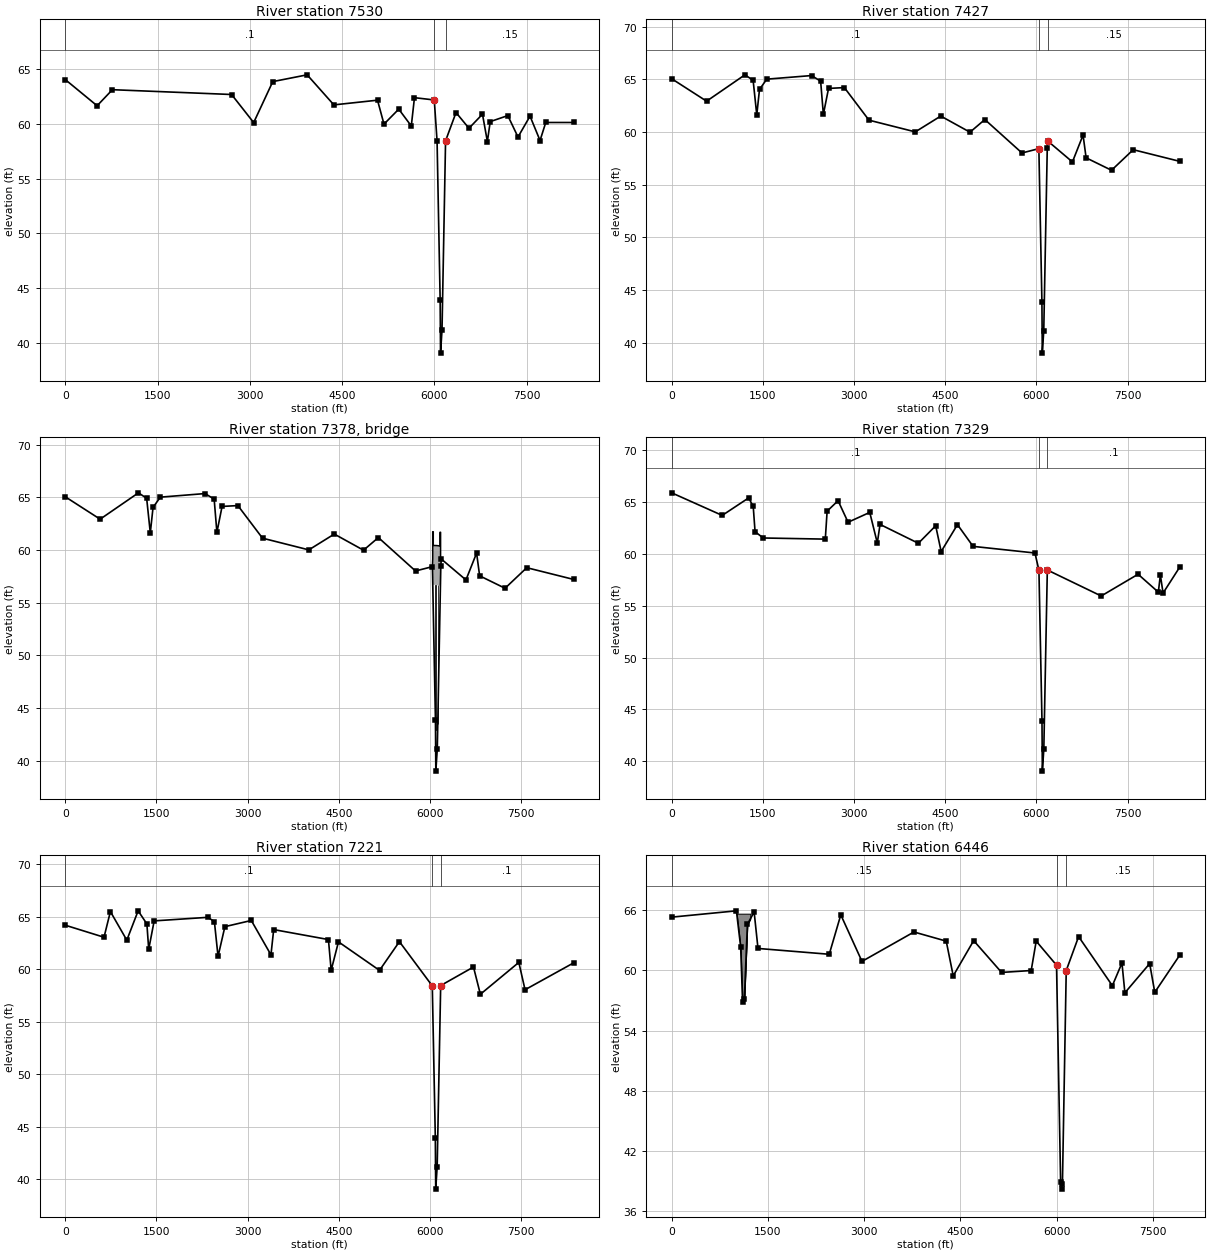
Type RM Length L Ch R = 1 ,7530    ,102.07,102.09,101.76
BEGIN DESCRIPTION:
 7529.556
END DESCRIPTION:
XS GIS Cut Line= 6
     3072065.194    13802306.465     3078056.368     13802504.25
     3078286.382    13802505.312     3078964.764    13802543.523
     3079846.427    13802604.845     3080318.392    13802629.871
#Sta/Elev= 30
       0   64.06  518.44   61.66  766.66   63.13 2703.74   62.69 3062.69   60.12
 3372.96   63.87 3931.46   64.49 4365.84   61.74    5075   62.17 5180.06   59.98
 5420.21   61.35 5623.85   59.81 5675.37    62.4 5997.34   62.19 6042.78   58.42
 6092.78   43.91 6099.05   39.03 6123.16   41.15  6180.9   58.45 6350.69   61.04
 6561.11    59.6 6780.54   60.89 6860.15   58.39 6906.66   60.21 7192.38   60.76
 7357.79    58.8 7553.24   60.71 7716.09   58.48 7808.81   60.13 8260.34   60.13
#Mann= 3 , 0 , 0
       0      .1       0 5997.34     .04       0  6180.9     .15       0
#XS Ineff= 2 , 0
       0    5991            6309       0
Permanent Ineff=
       T       T
Bank Sta=5997.34,6180.9
XS Rating Curve= 0
Exp/Cntr=.5,.3

Type RM Length L Ch R = 1 ,7427    ,98.8,98.89,98.8
BEGIN DESCRIPTION:
 7427.462
END DESCRIPTION:
XS GIS Cut Line= 6
     3072063.324    13802408.465     3078054.498     13802606.25
     3078962.894    13802632.537     3079395.025    13802771.684
     3079844.557    13802960.112     3080349.194    13803076.068
#Sta/Elev= 30
       0   65.05  574.48   62.92 1204.82   65.42 1339.89    64.9 1399.92   61.62
 1444.94   64.04 1565.01   65.01  2300.4   65.35 2450.48   64.82  2495.5   61.67
 2580.59   64.13 2840.68   64.21  3245.9   61.12 4007.86   60.01 4426.73   61.51
 4907.65   59.98 5151.91   61.18 5762.77   58.01 6040.78   58.42 6090.78   43.91
 6097.05   39.03 6121.16   41.15  6178.9   58.45 6187.44   59.14  6592.7   57.16
 6767.82   59.71 6817.85   57.55  7235.9   56.37 7593.09   58.32  8362.5   57.21
#Mann= 3 , 0 , 0
       0      .1       0 6040.78     .04       0 6187.44     .15       0
#XS Ineff= 2 , 0
       0    5992            6308       0
Permanent Ineff=
       T       T
Bank Sta=6040.78,6187.44
XS Rating Curve= 0
Exp/Cntr=.5,.3

Type RM Length L Ch R = 3 ,7378    ,,,
BEGIN DESCRIPTION:
Belfort Bridge
END DESCRIPTION:
Bridge Culvert--1,0,-1,-1, 0
Deck Dist Width WeirC Skew NumUp NumDn MinLoCord MaxHiCord MaxSubmerge Is_Ogee
5,90,2.6,0, 11, 11, , , .95, 0, 0,0,,
 6040.78 6045.63 6045.63 6055.05 6055.05 6111.28 6165.85 6165.85 6175.27 6175.27
 6187.44
   58.44   59.16   61.73   61.73   60.43   60.42   60.38   61.68   61.68   59.28
   59.16
     -.2     -.2     -.2     -.2   56.71   56.67   56.63     -.2     -.2     -.2
     -.2
    6036 6046.64 6046.64 6056.06 6056.06 6112.29    6166 6166.86 6176.28 6176.28
    6185
   58.43   59.28   61.73   61.73   60.43   60.42   60.38   61.68   61.68   59.28
   58.43
     -.2     -.2     -.2     -.2   56.71   56.67   56.63     -.2     -.2     -.2
     -.2
Pier Skew, UpSta & Num, DnSta & Num=  ,6091.98, 2 ,6092.99, 2 , 0 , 0 , 0 ,,
     1.4     1.4
       0     100
     1.4     1.4
       0     100
Pier Skew, UpSta & Num, DnSta & Num=  ,6128.92, 2 ,6129.93, 2 , 0 , 0 , 0 ,,
     1.4     1.4
       0     100
     1.4     1.4
       0     100
BR Coef=-1 , 1 , 1 ,1.25, 0 ,,,.8,-1,2,0,
WSPro=,,,, 1 ,,,, 0 ,,,, 0 ,,,,-1 ,-1 ,-1 , 0 , 0 , 0 , 0 , 0
BC Design=,, 0 ,, 0 ,,,,,,

Type RM Length L Ch R = 1 ,7329    ,107.21,107.3,107.21
BEGIN DESCRIPTION:
7328.577  Survey
END DESCRIPTION:
XS GIS Cut Line= 6
     3072061.525     13802507.26     3078052.699    13802705.045
     3078961.094    13802731.332     3079393.225    13802870.479
     3079842.758    13803058.907     3080347.394    13803174.863
#Sta/Elev= 30
       0    65.9  831.42   63.72 1266.65   65.41 1341.69   64.58  1371.7   62.15
 1505.59   61.54 2527.32   61.43 2557.33   64.13 2737.43   65.14 2901.83   63.06
 3258.64   64.01 3382.75   61.06  3427.8   62.85 4058.13   61.03 4343.28   62.72
 4433.33   60.23 4701.42   62.83 4958.61   60.73 5976.12   60.09 6041.78   58.42
 6091.78   43.91 6098.05   39.03 6122.16   41.15  6179.9   58.45 7066.38   55.94
 7672.93   58.04 8006.11   56.31  8039.4   57.96 8084.03   56.22  8362.5   58.77
#Mann= 3 , 0 , 0
       0      .1       0 6041.78     .04       0  6179.9      .1       0
#XS Ineff= 2 , 0
       0    5993            6302       0
Permanent Ineff=
       T       T
Bank Sta=6041.78,6179.9
XS Rating Curve= 0
Exp/Cntr=.5,.3

Type RM Length L Ch R = 1 ,7221    ,775.8,775.18,774.3
BEGIN DESCRIPTION:
 7221.274
END DESCRIPTION:
XS GIS Cut Line= 6
     3072059.549    13802614.465     3078050.723     13802812.25
     3078959.119    13802838.537      3079391.25    13802977.684
     3079840.782    13803166.112     3080345.419    13803282.068
#Sta/Elev= 30
       0   64.21  638.29   63.06  743.35   65.51 1013.48   62.78 1199.64   65.58
 1343.66   64.33 1373.68   61.91 1463.37   64.62 2347.65   64.96 2454.25   64.55
 2514.28   61.23  2626.9   64.07 3061.29   64.66 3384.75   61.38 3429.77   63.79
 4330.25   62.84 4375.27   59.91 4495.34   62.62 5170.69    59.9 5497.91   62.64
 6038.78   58.42 6088.78   43.91 6095.05   39.03 6119.16   41.15  6176.9   58.45
 6716.56   60.22 6829.95   57.62 7462.64   60.66 7564.66   58.05  8362.5   60.61
#Mann= 3 , 0 , 0
       0      .1       0 6038.78     .04       0  6176.9      .1       0
#XS Ineff= 2 , 0
       0    5993            6286       0
Permanent Ineff=
       T       T
Bank Sta=6038.78,6176.9
XS Rating Curve= 0
Exp/Cntr=.3,.1

Type RM Length L Ch R = 1 ,6446    ,890.09,891.19,892.94
BEGIN DESCRIPTION:
6446.097  Survey
END DESCRIPTION:
XS GIS Cut Line= 5
     3072057.639    13803369.522     3077226.505    13803557.456
     3078018.125    13803587.371     3078246.601    13803586.725
      3079975.16    13803692.118
#Sta/Elev= 30
       0   65.31 1009.22   65.94 1075.57   62.34 1105.59   56.82 1133.83    57.2
 1180.56    64.6 1285.71   65.82 1345.75   62.19 2456.48   61.61  2636.6   65.54
 2966.82    60.9 3777.36   63.83 4280.23   62.92 4389.27   59.46 4707.97   62.97
 5143.26    59.8 5604.88   59.99 5682.88   62.92 5999.84   60.52 6063.81   38.87
 6077.62    38.2 6091.96   38.76 6151.15   59.99 6344.13   63.37  6870.1   58.48
 7019.93   60.74 7065.46   57.77 7452.03   60.68 7531.33   57.82 7924.72   61.56
#Mann= 3 , 0 , 0
       0     .15       0 5999.84     .04       0 6151.15     .15       0
#XS Ineff= 2 , 0
       0    5920            6213       0
Permanent Ineff=
       T       T
#Block Obstruct= 2 ,-1
  965.48 1222.01   65.61  983.04 1226.17   65.66
Bank Sta=5999.84,6151.15
XS Rating Curve= 0
Exp/Cntr=.3,.1

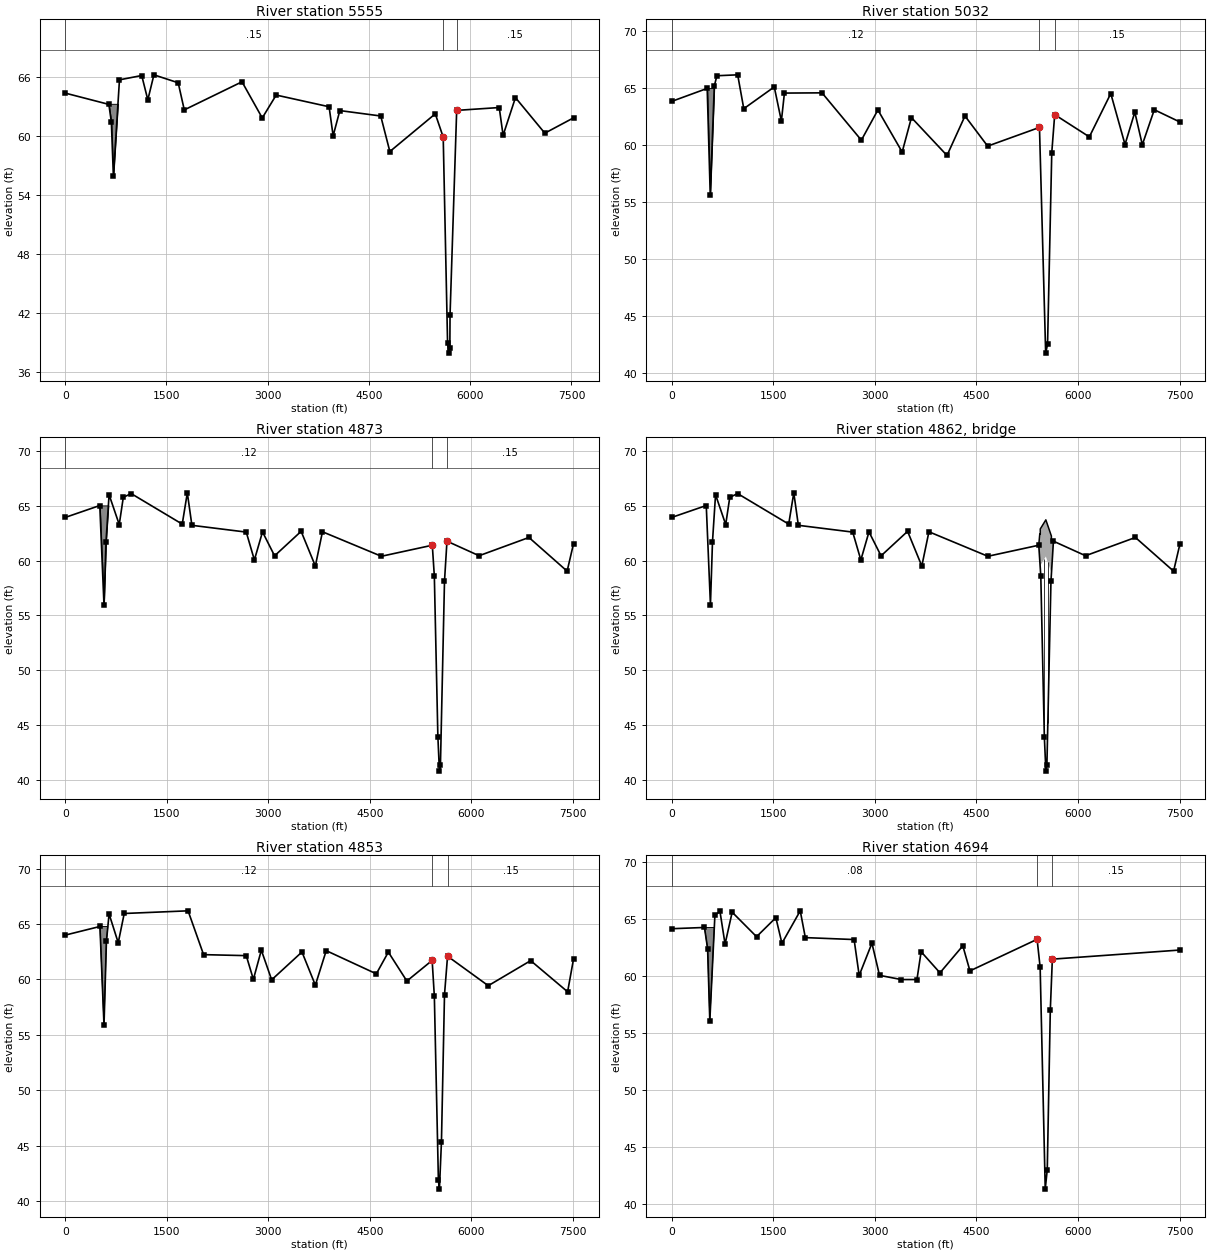
Type RM Length L Ch R = 1 ,5555    ,524.89,523.1,521.52
BEGIN DESCRIPTION:
5554.910  Survey
END DESCRIPTION:
XS GIS Cut Line= 5
     3072418.702     13804401.72      3077253.08    13804467.047
     3077986.864    13804476.681     3078212.004    13804478.955
     3079947.406    13804543.299
#Sta/Elev= 30
       0   64.36  646.82   63.21  683.86    61.4  713.86   55.88  803.87   65.71
 1133.44   66.15 1223.91   63.67 1313.92   66.22 1673.95   65.41 1763.96   62.65
 2619.04   65.51 2919.06   61.83 3125.53   64.16 3909.15   62.97 3969.16   60.01
 4068.36   62.58 4674.22   62.03 4809.24   58.41 5482.34   62.25 5599.83   59.88
 5664.36   38.92 5681.85   37.89 5698.09   38.38 5701.01   41.78 5799.32    62.6
 6429.75   62.89 6486.92   60.06 6669.91    63.9 7105.21   60.28 7530.41   61.84
#Mann= 3 , 0 , 0
       0     .15       0 5599.83     .04       0 5799.32     .15       0
#XS Ineff= 2 , 0
       0    5476            5844       0
Permanent Ineff=
       T       T
#Block Obstruct= 1 ,-1
  632.74  814.54   63.27
Bank Sta=5599.83,5799.32
XS Rating Curve= 0
Exp/Cntr=.3,.1

Type RM Length L Ch R = 1 ,5032    ,159.01,159.08,159.11
BEGIN DESCRIPTION:
 5031.811
END DESCRIPTION:
XS GIS Cut Line= 5
     3072548.082    13804811.529     3077196.725    13804947.158
     3077957.262     13805001.11     3078185.569    13804999.952
     3080048.039    13805111.918
#Sta/Elev= 30
       0   63.84  524.64   64.98  569.66   55.63  629.69    65.2  668.22   66.09
  974.83   66.17 1064.87    63.2 1515.06   65.11 1620.11   62.12 1665.13   64.57
 2220.36   64.59 2801.34   60.44 3045.71   63.09 3404.17    59.4 3540.92   62.42
 4066.15    59.1 4331.61   62.56 4666.44   59.92 5431.82   61.56 5523.31   41.77
 5551.22   42.54 5613.31   59.34 5656.71   62.68 6168.33   60.73 6484.83   64.53
 6695.21   60.06 6839.84    62.9 6950.67   60.04 7127.63   63.11 7507.21   62.03
#Mann= 3 , 0 , 0
       0     .12       0 5431.82     .04       0 5656.71     .15       0
#XS Ineff= 2 , 0
       0    5351            5722       0
Permanent Ineff=
       T       T
#Block Obstruct= 1 ,-1
  518.49  671.68   65.02
Bank Sta=5431.82,5656.71
XS Rating Curve= 0
Exp/Cntr=.5,.3

Type RM Length L Ch R = 1 ,4873    ,19.97,20.01,20.02
BEGIN DESCRIPTION:
 4872.731
END DESCRIPTION:
XS GIS Cut Line= 5
     3072544.871    13804970.529     3077193.514    13805106.158
     3077954.051     13805160.11     3078182.358    13805158.952
     3080044.828    13805270.918
#Sta/Elev= 30
       0   63.96  510.77   65.05   572.6   55.98  602.89   61.75   647.9   66.04
  797.97   63.31  857.99    65.8  974.49   66.14 1728.36   63.35  1803.4   66.21
 1871.02   63.24 2673.77   62.62 2793.82   60.07 2913.87   62.64 3092.15   60.45
 3484.11   62.69  3694.2   59.52 3799.24   62.65 4669.59   60.41 5421.52   61.42
 5451.52   58.59 5503.67   43.93 5526.52   40.77 5541.52   41.31 5601.52   58.13
 5637.99   61.79 6112.37   60.46  6848.7   62.13 7412.44   59.05 7507.21   61.56
#Mann= 3 , 0 , 0
       0     .12       0 5421.52     .04       0 5637.99     .15       0
#XS Ineff= 2 , 0
       0    5243            5697       0
Permanent Ineff=
       T       T
#Block Obstruct= 1 ,-1
  509.84  639.71   65.06
Bank Sta=5421.52,5637.99
XS Rating Curve= 0
Exp/Cntr=.5,.3

Type RM Length L Ch R = 3 ,4862    ,,,
BEGIN DESCRIPTION:
Crosswalk Bridge at Bankside
END DESCRIPTION:
Bridge Culvert--1,0,-1,-1, 0
Deck Dist Width WeirC Skew NumUp NumDn MinLoCord MaxHiCord MaxSubmerge Is_Ogee
5,10,2.6,0, 8, 8, , , .95, 0, 0,0,,
    5420  5435.9 5443.74 5443.74  5525.9 5608.07 5608.07    5640
   61.35   62.44   62.44   62.91   63.74   62.26   61.77   61.77
     -.2     -.2     -.2   59.56   60.39   58.91     -.2     -.2
 5419.17 5434.98 5442.82 5442.82 5524.98 5607.15 5607.15    5630
   61.83   62.44   62.44   62.91   63.74   62.26   61.77   61.77
     -.2     -.2     -.2   59.56   60.39   58.91     -.2     -.2
Pier Skew, UpSta & Num, DnSta & Num=  ,5500.52, 2 ,5499.6, 2 , 0 , 0 , 0 ,,
       1       1
       0     100
       1       1
       0     100
Pier Skew, UpSta & Num, DnSta & Num=  ,5555.29, 2 ,5554.37, 2 , 0 , 0 , 0 ,,
       1       1
       0     100
       1       1
       0     100
BR Coef=-1 , 1 , 1 ,1.25, 0 ,,,.8,-1,2,0,
WSPro=,,,, 1 ,,,, 0 ,,,, 0 ,,,,-1 ,-1 ,-1 , 0 , 0 , 0 , 0 , 0
BC Design=,, 0 ,, 0 ,,,,,,

Type RM Length L Ch R = 1 ,4853    ,159.07,159.07,159.13
BEGIN DESCRIPTION:
 4852.719
END DESCRIPTION:
XS GIS Cut Line= 5
     3072544.793    13804990.529     3077193.436    13805126.158
     3077953.973     13805180.11      3078182.28    13805178.952
      3080044.75    13805290.918
#Sta/Elev= 30
       0      64  512.93   64.78  572.95   55.87  608.75   63.45  647.98   65.91
  783.04   63.31  871.52   65.95 1814.42   66.19 2043.58   62.24 2673.84   62.15
 2778.89   60.01 2896.44   62.64    3049   59.97 3496.52   62.48 3694.28   59.49
 3854.79    62.6 4594.66   60.51 4772.25   62.47 5045.67   59.86 5419.17   61.72
  5451.6   58.49  5511.6   41.89  5526.6    41.1  5556.6   45.38  5601.6   58.63
 5646.61    62.1 6247.69   59.44 6874.26    61.7  7419.8   58.89 7507.21   61.85
#Mann= 3 , 0 , 0
       0     .12       0 5419.17     .04       0 5646.61     .15       0
#XS Ineff= 2 , 0
       0    5230            5690       0
Permanent Ineff=
       T       T
#Block Obstruct= 1 ,-1
  511.26  649.82   64.78
Bank Sta=5419.17,5646.61
XS Rating Curve= 0
Exp/Cntr=.5,.3

Type RM Length L Ch R = 1 ,4694    ,58.01,58.01,58.03
BEGIN DESCRIPTION:
 4693.65
END DESCRIPTION:
XS GIS Cut Line= 5
     3072539.486    13805149.529     3077188.129    13805285.158
     3077948.666     13805339.11     3078176.973    13805337.952
     3080039.443    13805449.918
#Sta/Elev= 30
       0   64.14  484.38   64.25  530.75   62.39  563.25   56.04  638.29   65.32
  713.32   65.66  788.35   62.79  893.39   65.59 1253.55   63.44 1538.67   65.11
 1628.22   62.86 1898.82   65.71 1973.85   63.36 2694.16   63.19 2769.19   60.04
 2957.55   62.87 3069.32   60.05 3390.36   59.68 3622.22   59.68 3684.05   62.12
 3962.28   60.27 4299.84   62.64 4404.89   60.44 5396.86   63.21  5441.9   60.74
  5516.9   41.29  5546.9   43.01 5591.91   57.02 5621.91   61.47 7507.21   62.27
#Mann= 3 , 0 , 0
       0     .08       0 5396.86     .04       0 5621.91     .15       0
#XS Ineff= 2 , 0
       0    5151            5663       0
Permanent Ineff=
       T       T
#Block Obstruct= 1 ,-1
  483.65  640.29   64.25
Bank Sta=5396.86,5621.91
XS Rating Curve= 0
Exp/Cntr=.3,.1

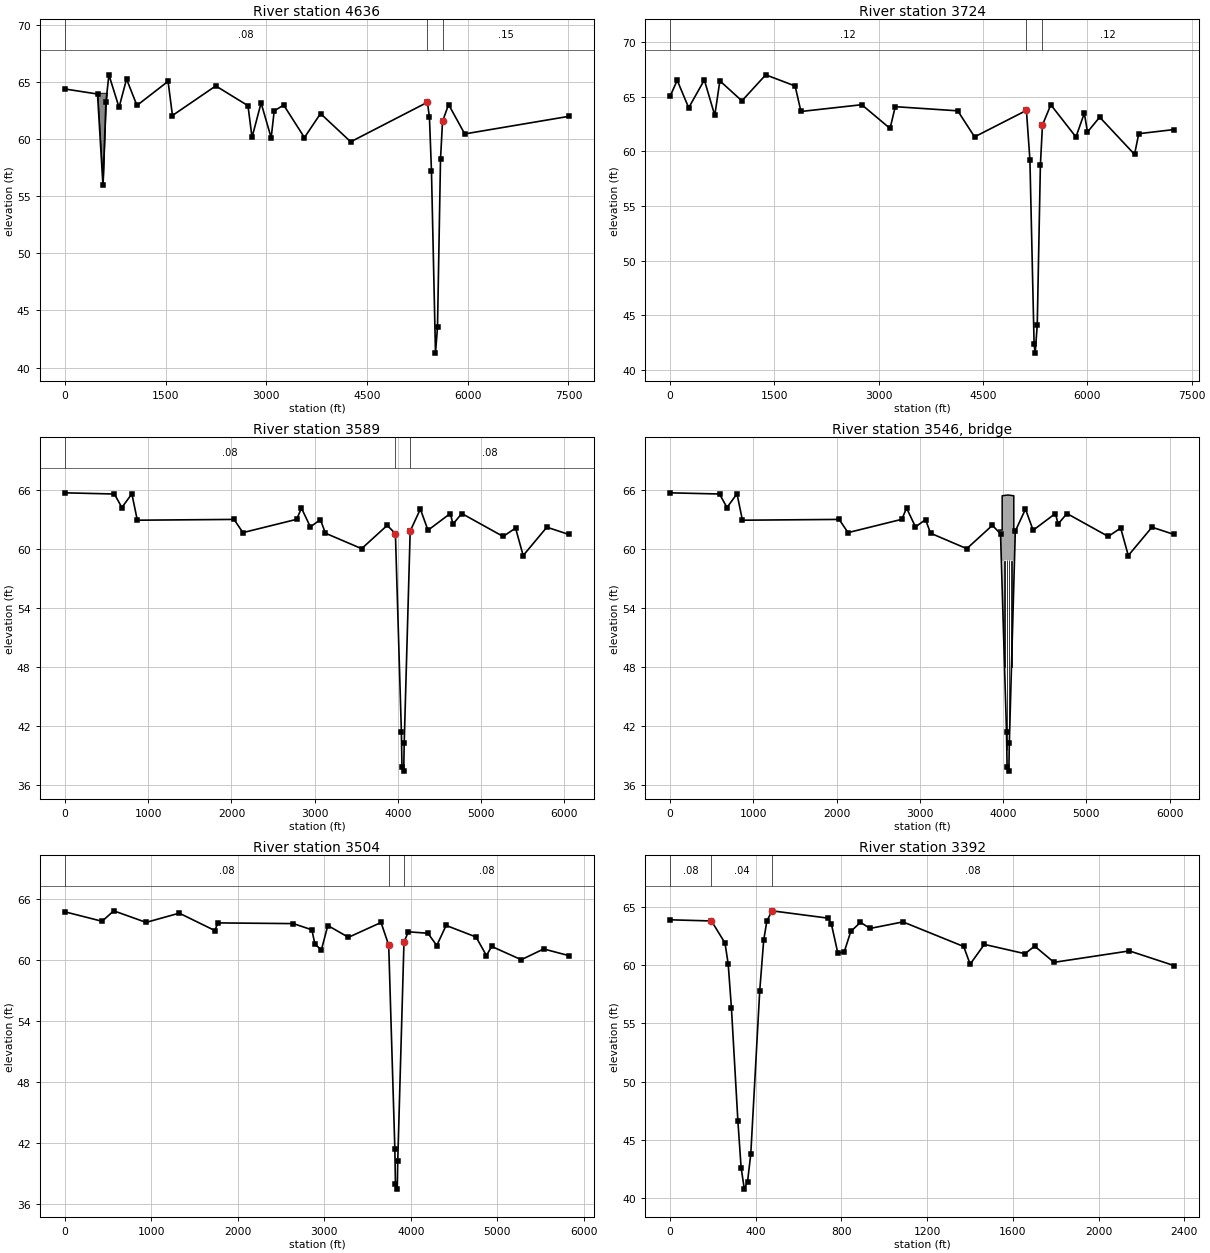
Type RM Length L Ch R = 1 ,4636    ,921.7,911.6,903.28
BEGIN DESCRIPTION:
4635.643  Survey
END DESCRIPTION:
XS GIS Cut Line= 5
     3072537.589    13805207.511     3077186.232     13805343.14
     3077946.769    13805397.092     3078175.076    13805395.934
     3080037.546      13805507.9
#Sta/Elev= 30
       0   64.37  484.25   63.93  565.15   55.99  610.17   63.25  654.28   65.61
  805.25   62.76  917.06   65.24 1071.63   62.93 1535.35   65.04 1600.59   62.05
 2245.87   64.64 2725.57   62.91  2786.1   60.14 2921.15   63.15 3071.22    60.1
 3116.24   62.45 3257.12   62.97 3566.43   60.12 3806.53   62.22 4255.85   59.75
 5398.76   63.21  5428.8   61.88  5458.8   57.21  5518.8   41.26  5548.8   43.55
  5593.8   58.26  5623.8   61.54 5713.93   63.01 5954.37   60.44 7507.21   61.98
#Mann= 3 , 0 , 0
       0     .08       0 5398.76     .04       0  5623.8     .15       0
#XS Ineff= 2 , 0
       0    5130            5662       0
Permanent Ineff=
       T       T
#Block Obstruct= 1 ,-1
  464.81   657.2   64.04
Bank Sta=5398.76,5623.8
XS Rating Curve= 0
Exp/Cntr=.3,.1

Type RM Length L Ch R = 1 ,3724    ,135.04,134.98,134.95
BEGIN DESCRIPTION:
 3724.043
END DESCRIPTION:
XS GIS Cut Line= 5
     3072775.363    13806185.028      3077151.19    13806281.193
     3077911.837     13806318.11     3078136.692    13806298.405
     3080014.523    13806446.914
#Sta/Elev= 30
       0   65.03  101.93   66.49   267.2   63.98  492.26   66.52  642.29   63.28
  715.56   66.44 1032.39   64.61 1375.21   66.99 1797.57   65.97 1881.46   63.64
 2755.88   64.26  3162.9   62.09 3237.92   64.08 4136.55    63.7  4378.2   61.32
 5123.98   63.74 5174.23   59.23 5234.46   42.37 5249.51   41.56 5279.63   44.12
  5324.8   58.72 5354.92   62.41 5474.94   64.25 5836.42   61.31  5956.8   63.49
 6001.94   61.76 6177.51   63.12 6679.04   59.72 6739.23   61.61 7247.84   61.99
#Mann= 3 , 0 , 0
       0     .12       0 5123.98     .04       0 5354.92     .12       0
#XS Ineff= 2 , 0
       0    4881            5399       0
Permanent Ineff=
       T       T
Bank Sta=5123.98,5354.92
XS Rating Curve= 0
Exp/Cntr=.5,.3

Type RM Length L Ch R = 1 ,3589    ,84.31,85.22,85.12
BEGIN DESCRIPTION:
 3589.064
END DESCRIPTION:
XS GIS Cut Line= 5
     3073964.235    13806356.754     3077145.208    13806416.103
     3077905.855     13806453.02      3078130.71    13806433.315
     3080011.211    13806581.992
#Sta/Elev= 30
       0    65.7  593.37   65.58  683.38   64.21   803.4    65.6  868.88   62.92
 2030.75      63 2137.77   61.66 2783.75   63.01 2841.01   64.15 2948.03   62.24
  3068.8   62.98 3128.81    61.6 3564.27   60.03 3871.69    62.4 3969.82   61.54
 4041.58   41.44  4048.5    37.9 4069.56   37.44 4075.36   40.26 4147.26   61.81
 4269.65   64.05 4361.17    61.9  4629.1    63.6 4661.78   62.53 4767.44    63.6
 5263.98   61.27 5413.36   62.12 5504.73   59.33 5789.14   62.21 6055.16   61.47
#Mann= 3 , 0 , 0
       0     .08       0 3969.82     .04       0 4147.26     .08       0
#XS Ineff= 2 , 0
       0    3756            4210       0
Permanent Ineff=
       T       T
Bank Sta=3969.82,4147.26
XS Rating Curve= 0
Exp/Cntr=.5,.3

Type RM Length L Ch R = 3 ,3546    ,,,
BEGIN DESCRIPTION:
Willowbend Bridge
END DESCRIPTION:
Bridge Culvert--1,0,-1,-1, 0
Deck Dist Width WeirC Skew NumUp NumDn MinLoCord MaxHiCord MaxSubmerge Is_Ogee
5,52,2.6,0, 7, 7, , , .95, 0, 0,0,,
 3949.53 3989.34 3989.34 4059.25 4129.16 4129.16 4147.26
   61.92   61.92    65.4   65.48    65.4   61.87   61.81
       0       0   58.79   58.87   58.79       0       0
  3722.3 3762.11 3762.11 3832.02 3901.93 3901.93 3920.26
   61.92   61.92    65.4   65.48    65.4   61.87   61.81
       0       0   58.79   58.87   58.79       0       0
Pier Skew, UpSta & Num, DnSta & Num=  ,4018.02, 2 ,3790.79, 2 , 0 , 0 , 0 ,,
       2       2
       0     100
       2       2
       0     100
Pier Skew, UpSta & Num, DnSta & Num=  ,4045.27, 2 ,3818.04, 2 , 0 , 0 , 0 ,,
       2       2
       0     100
       2       2
       0     100
Pier Skew, UpSta & Num, DnSta & Num=  ,4073.23, 2 ,3846, 2 , 0 , 0 , 0 ,,
       2       2
       0     100
       2       2
       0     100
Pier Skew, UpSta & Num, DnSta & Num=  ,4101.2, 2 ,3873.97, 2 , 0 , 0 , 0 ,,
       2       2
       0     100
       2       2
       0     100
BR Coef=-1 , 1 , 1 ,1.25, 0 ,,,.8,-1,2,0,
WSPro=,,,, 1 ,,,, 0 ,,,, 0 ,,,,-1 ,-1 ,-1 , 0 , 0 , 0 , 0 , 0
BC Design=,, 0 ,, 0 ,,,,,,

Type RM Length L Ch R = 1 ,3504    ,113.1,112.06,111.92
BEGIN DESCRIPTION:
3503.840  Survey
END DESCRIPTION:
XS GIS Cut Line= 5
       3074188.8    13806436.012     3077147.796    13806500.641
     3077908.443    13806537.558     3078133.298    13806517.853
     3080009.268    13806661.235
#Sta/Elev= 30
       0   64.78   428.8   63.85  563.83   64.88  937.92   63.74 1321.38   64.65
 1734.11   62.93  1766.2   63.69  2640.5   63.62 2855.24   63.01 2889.39   61.62
 2964.41   61.01  3039.5   63.43 3278.37   62.27 3655.22   63.73  3743.6   61.49
 3814.58   41.44  3821.5    37.9 3842.56   37.44 3848.36   40.26 3920.26   61.81
 3971.23   62.81 4196.89   62.67  4299.4   61.46  4407.5   63.44 4753.51    62.3
 4873.86   60.47 4934.03   61.37 5276.72   60.06 5535.78   61.12  5828.4   60.46
#Mann= 3 , 0 , 0
       0     .08       0  3743.6     .04       0 3920.26     .08       0
#XS Ineff= 2 , 0
       0    3585            4000       0
Permanent Ineff=
       T       T
Bank Sta=3743.6,3920.26
XS Rating Curve= 0
Exp/Cntr=.5,.3

Type RM Length L Ch R = 1 ,3392    ,276.75,288.11,297.94
BEGIN DESCRIPTION:
 3391.781
END DESCRIPTION:
XS GIS Cut Line= 4
     3077661.489    13806647.553     3077897.977     13806649.93
     3078122.832    13806630.225     3080005.954    13806796.379
#Sta/Elev= 30
       0   63.89  193.01   63.79   256.1    61.9  271.16   60.09  286.21   56.33
  316.33   46.64  331.39   42.63  346.44   40.78   361.5   41.43  376.56   43.79
  418.28   57.79  436.79   62.13  451.85    63.8  475.86   64.66  737.95   64.03
  753.01   63.51  783.13   61.02  813.24   61.16  843.36   62.89  888.53   63.67
  933.71   63.15 1086.94   63.71  1370.4    61.6 1400.52   60.08 1466.79   61.78
 1656.51   60.98 1701.68   61.63 1792.03   60.24 2143.93   61.22 2352.65   59.96
#Mann= 3 , 0 , 0
       0     .08       0  193.01     .04       0  475.86     .08       0
#XS Ineff= 2 , 0
       0     187             533       0
Permanent Ineff=
       T       T
Bank Sta=193.01,475.86
XS Rating Curve= 0
Exp/Cntr=.3,.1