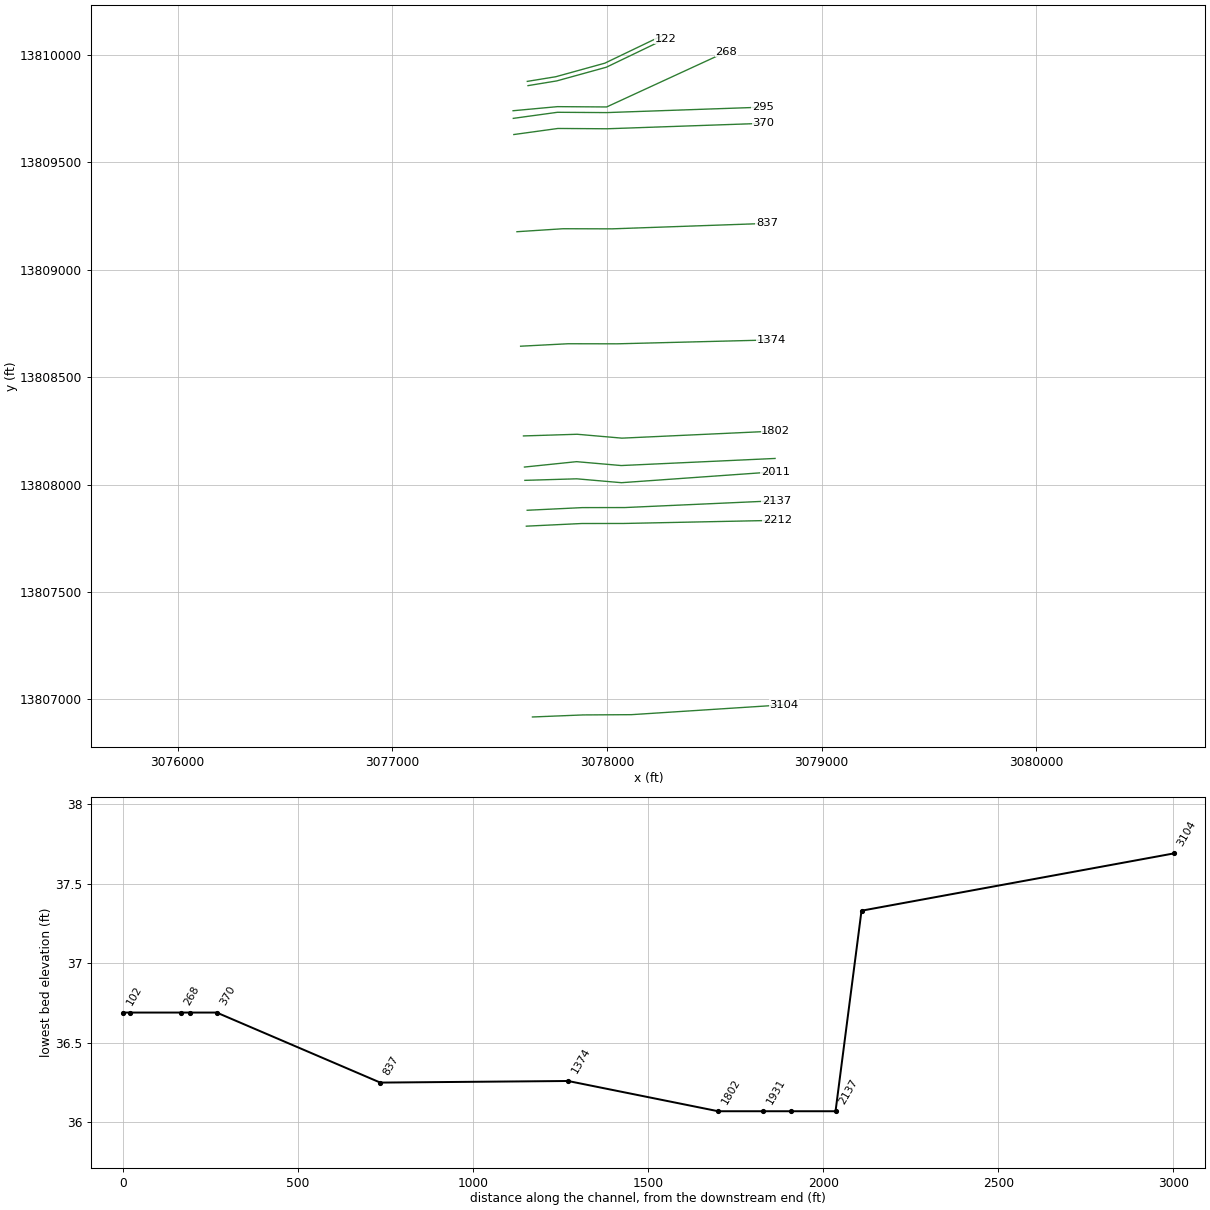
HEC-RAS study D140-00-00.prj: D140-00-00

--- D140-00-00.g02 (geometry) --- (continued)

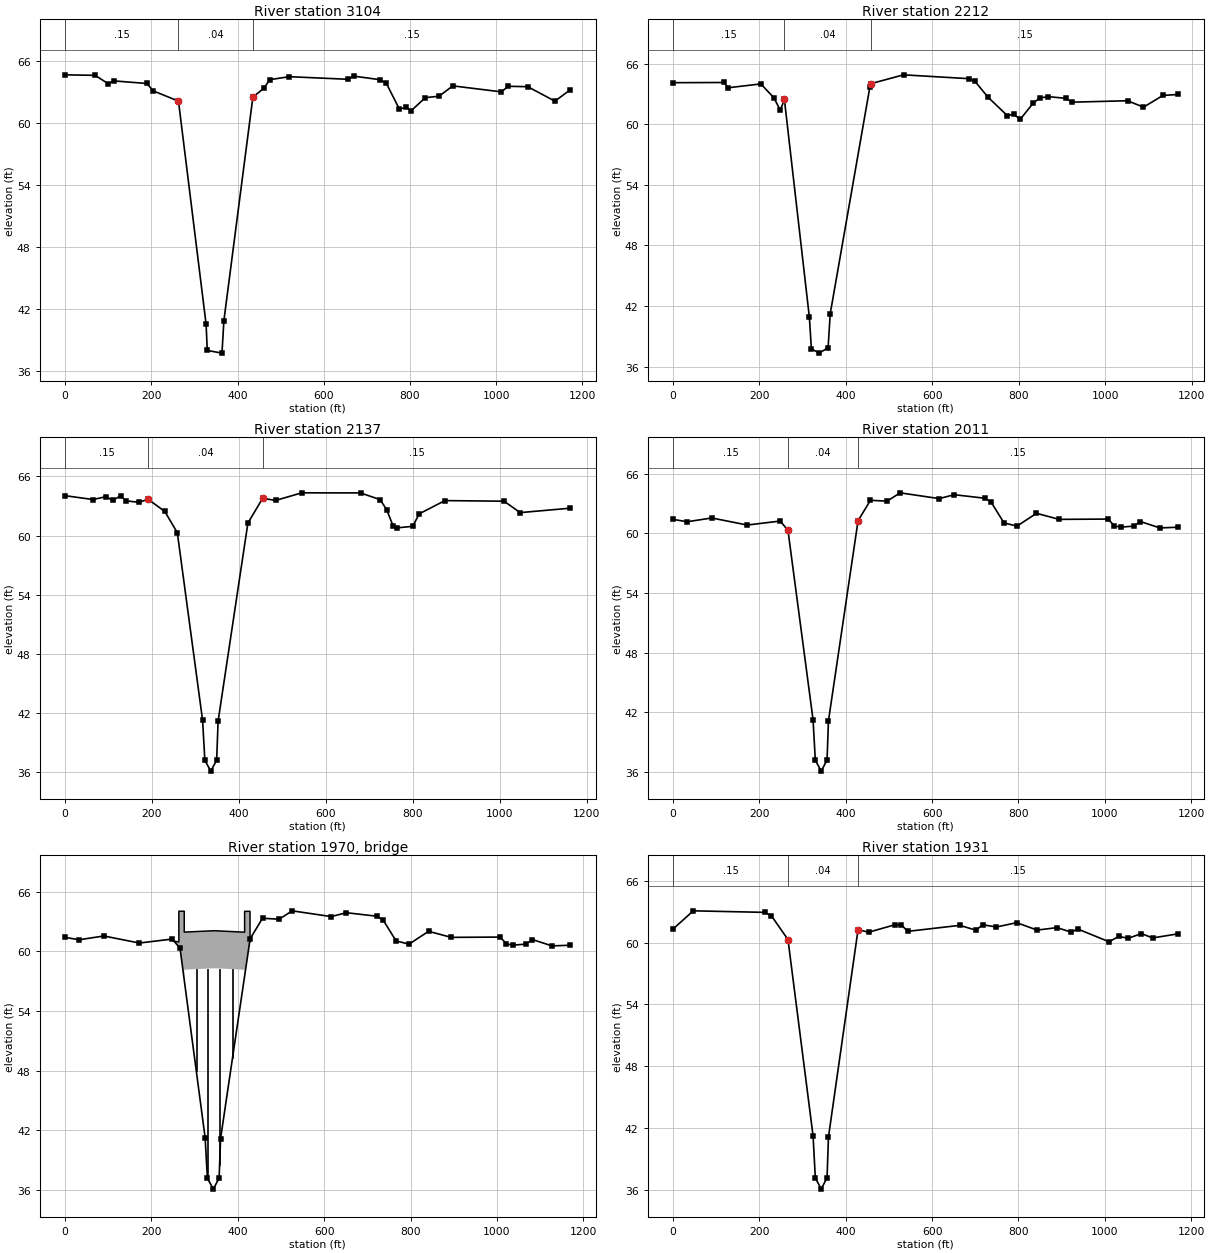
Type RM Length L Ch R = 1 ,3104    ,890.73,892.05,891.27
BEGIN DESCRIPTION:
3103.669  Survey
END DESCRIPTION:
XS GIS Cut Line= 4
     3077652.865    13806917.249     3077888.403    13806926.798
     3078113.657    13806928.018     3078823.365    13806973.871
#Sta/Elev= 30
       0   64.65   69.69    64.6   99.72    63.8   114.1   64.06  189.79   63.81
   204.8   63.09  263.09    62.1   327.2   40.47  329.86   37.95  364.01   37.69
  368.44   40.84  435.69    62.5  460.99   63.34  474.86   64.18  519.95   64.47
  655.24   64.22  670.27   64.52  730.39   64.18  745.42   63.81  775.49   61.33
  790.52   61.51  803.12   61.18  835.61   62.44   867.4   62.58  899.54   63.58
 1012.02      63 1028.09   63.54 1073.36    63.5 1136.24    62.1 1172.18   63.21
#Mann= 3 , 0 , 0
       0     .15       0  263.09     .04       0  435.69     .15       0
#XS Ineff= 2 , 0
       0     241             521       0
Permanent Ineff=
       T       T
Bank Sta=263.09,435.69
XS Rating Curve= 0
Exp/Cntr=.3,.1

Type RM Length L Ch R = 1 ,2212    ,73.82,74.17,74.14
BEGIN DESCRIPTION:
2211.617  Survey
END DESCRIPTION:
XS GIS Cut Line= 4
     3077624.445    13807805.973     3077881.902    13807818.317
     3078079.867    13807818.596     3078793.076    13807833.216
#Sta/Elev= 30
       0   64.14  117.28   64.16   128.2   63.64  203.29   64.02  233.32   62.65
  248.34   61.41  257.75   62.48  315.59   40.87  320.22   37.76  338.23   37.33
   358.9   37.87  363.76   41.23  455.72   63.76  458.35   64.05  533.37   64.92
  684.18   64.54   698.4   64.29  728.41   62.72  773.42   60.88  788.42   61.01
  803.42   60.51  833.43   62.12  848.43   62.62  867.98   62.76  908.45   62.59
  923.45   62.21 1051.79   62.35 1088.48   61.71 1133.49   62.88 1169.08   62.97
#Mann= 3 , 0 , 0
       0     .15       0  257.75     .04       0  458.35     .15       0
#XS Ineff= 2 , 0
       0     189             518       0
Permanent Ineff=
       T       T
Bank Sta=257.75,458.35
XS Rating Curve= 0
Exp/Cntr=.3,.1

Type RM Length L Ch R = 1 ,2137    ,135.87,126.4,115.96
BEGIN DESCRIPTION:
 2137.449
END DESCRIPTION:
XS GIS Cut Line= 4
     3077628.318    13807880.066     3077885.775     13807892.41
      3078083.74    13807892.688      3078789.86    13807924.481
#Sta/Elev= 30
       0   64.05   64.26   63.66   94.29   63.95  109.31   63.57  128.03   64.04
  139.34   63.53  169.38   63.38  191.12   63.68  229.45   62.45  258.29   60.29
  316.37   41.24  321.62   37.16  335.35   36.07  348.77   37.19  352.07   41.14
  420.58   61.26  454.48   63.78  484.51   63.57  544.57   64.34   679.7   64.33
  724.75   63.65  739.77   62.64  754.78   60.97  763.84   60.78  799.83   60.94
  814.84   62.21   873.9   63.55 1010.04   63.49 1046.85   62.33 1162.55   62.78
#Mann= 3 , 0 , 0
       0     .15       0  191.12     .04       0  454.48     .15       0
#XS Ineff= 2 , 0
       0     180             513       0
Permanent Ineff=
       T       T
Bank Sta=191.12,454.48
XS Rating Curve= 0
Exp/Cntr=.5,.3

Type RM Length L Ch R = 1 ,2011    ,77.16,80.22,80.02
BEGIN DESCRIPTION:
 2011.052
END DESCRIPTION:
XS GIS Cut Line= 4
     3077617.621    13808019.363     3077859.158     13808026.54
     3078067.345    13808008.476     3078785.104    13808059.406
#Sta/Elev= 30
       0    61.4   32.73   61.16   89.92   61.54  171.92   60.83  248.46   61.23
  266.29   60.29  324.37   41.24  329.62   37.16  343.35   36.07  356.77   37.19
  360.07   41.14  428.58   61.26  457.23   63.32  495.88   63.23  525.96   64.07
  616.18   63.49  651.46   63.88  721.45   63.53  736.48   63.15  766.56   61.04
  796.64   60.72  841.75   62.01  894.26    61.4 1007.56   61.43  1022.2   60.74
 1037.24   60.62 1067.31   60.72 1082.35   61.18 1127.47   60.54 1170.18   60.61
#Mann= 3 , 0 , 0
       0     .15       0  266.29     .04       0  428.58     .15       0
#XS Ineff= 2 , 0
       0     185             524       0
Permanent Ineff=
       T       T
Bank Sta=266.29,428.58
XS Rating Curve= 0
Exp/Cntr=.5,.3

Type RM Length L Ch R = 3 ,1970    ,,,
BEGIN DESCRIPTION:
Dumfries Bridge
END DESCRIPTION:
Bridge Culvert--1,0,-1,-1, 0
Deck Dist Width WeirC Skew NumUp NumDn MinLoCord MaxHiCord MaxSubmerge Is_Ogee
5,52,2.6,0, 11, 11, , , .95, 0, 0,0,,
     251   263.5   263.5     276     276  345.91  415.82  415.82  428.32  428.32
  428.32
   61.03   60.94   64.03   64.03   61.93   62.07   61.92   64.02   64.02   60.96
   61.02
       0       0       0       0   58.15   58.29   58.14       0       0       0
       0
     251   263.5   263.5     276     276  345.91  415.82  415.82  428.32  428.32
  428.32
   61.03   60.94   64.03   64.03   61.93   62.07   61.92   64.02   64.02   60.96
   61.02
       0       0       0       0   58.15   58.29   58.14       0       0       0
       0
Pier Skew, UpSta & Num, DnSta & Num=  ,303.96, 2 ,303.96, 2 , 0 , 0 , 0 ,,
       2       2
       0     100
       2       2
       0     100
Pier Skew, UpSta & Num, DnSta & Num=  ,329.93, 2 ,329.93, 2 , 0 , 0 , 0 ,,
       2       2
       0     100
       2       2
       0     100
Pier Skew, UpSta & Num, DnSta & Num=  ,357.89, 2 ,357.89, 2 , 0 , 0 , 0 ,,
       2       2
       0     100
       2       2
       0     100
Pier Skew, UpSta & Num, DnSta & Num=  ,387.86, 2 ,387.86, 2 , 0 , 0 , 0 ,,
       2       2
       0     100
       2       2
       0     100
BR Coef=-1 , 1 , 1 ,1.25, 0 ,,,.8,-1,2,0,
WSPro=,,,, 1 ,,,, 0 ,,,, 0 ,,,,-1 ,-1 ,-1 , 0 , 0 , 0 , 0 , 0
BC Design=,, 0 ,, 0 ,,,,,,

Type RM Length L Ch R = 1 ,1931    ,130.25,128.57,128.66
BEGIN DESCRIPTION:
1930.833  Survey
END DESCRIPTION:
XS GIS Cut Line= 4
     3077615.639    13808081.333     3077858.301    13808106.404
     3078066.488     13808088.34      3078782.92     13808121.37
#Sta/Elev= 30
       0   61.31   47.11   63.08  212.99   62.93  228.07   62.59  266.29   60.29
  324.37   41.24  329.62   37.16  343.35   36.07  356.77   37.19  360.07   41.14
  428.58   61.26  452.92      61     514   61.73  529.02   61.69  544.03   61.09
  664.16   61.67  701.49    61.2  717.23   61.73  748.71   61.51  795.94   61.93
  843.16   61.21   889.4   61.45  921.87   61.01  937.61   61.31 1009.53   60.08
 1032.06   60.59 1054.57   60.42 1084.61   60.87 1110.77   60.45 1170.12   60.85
#Mann= 3 , 0 , 0
       0     .15       0  266.29     .04       0  428.58     .15       0
#XS Ineff= 2 , 0
       0     189             520       0
Permanent Ineff=
       T       T
Bank Sta=266.29,428.58
XS Rating Curve= 0
Exp/Cntr=.5,.3

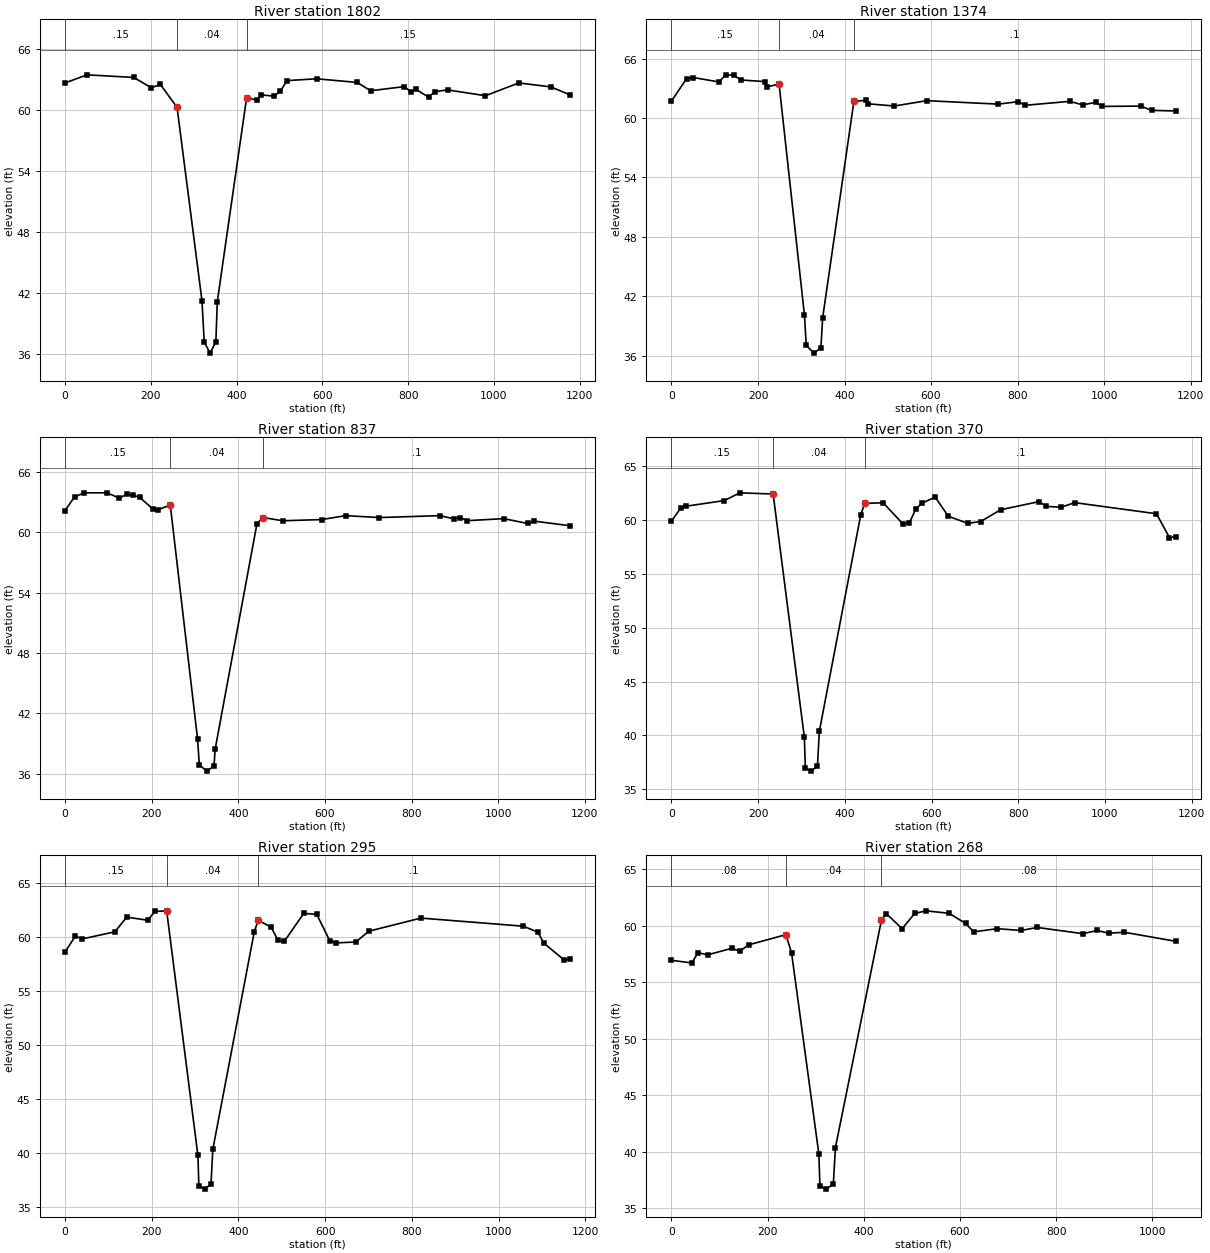
Type RM Length L Ch R = 1 ,1802    ,422.27,428.68,438.98
BEGIN DESCRIPTION:
 1802.262
END DESCRIPTION:
XS GIS Cut Line= 4
     3077611.003    13808226.289     3077861.386     13808234.02
     3078069.573    13808215.956     3078786.005    13808248.986
#Sta/Elev= 30
       0    62.7   51.52    63.5  160.31   63.24  201.59   62.22  222.25   62.56
  261.29   60.29  319.37   41.24  324.62   37.16  338.35   36.07  351.77   37.19
  355.07   41.14  423.58   61.26  447.92      61  457.39   61.53  487.43   61.39
  502.44    61.9  517.46   62.93  586.86   63.11  681.31   62.75  712.67   61.93
   791.5   62.34  807.24   61.79  817.78   62.07  847.81   61.31  862.83   61.85
  892.86   62.01   980.4   61.44 1058.03    62.7 1133.11   62.31 1176.66   61.54
#Mann= 3 , 0 , 0
       0     .15       0  261.29     .04       0  423.58     .15       0
#XS Ineff= 2 , 0
       0     196             516       0
Permanent Ineff=
       T       T
Bank Sta=261.29,423.58
XS Rating Curve= 0
Exp/Cntr=.3,.1

Type RM Length L Ch R = 1 ,1374    ,535.62,536.23,536.27
BEGIN DESCRIPTION:
1373.580  Survey
END DESCRIPTION:
XS GIS Cut Line= 4
     3077597.641    13808644.149     3077818.583    13808655.627
     3078047.978    13808655.304     3078763.463    13808673.384
#Sta/Elev= 30
       0   61.72   34.91   63.99   49.93    64.1  110.01   63.65  125.03   64.37
  144.18   64.33  160.03   63.85  215.15   63.69  221.24   63.16  248.67   63.43
   307.3   40.12  311.59   37.04  329.18   36.26  345.42   36.79  349.39   39.81
  421.73    61.7  450.64   61.79  455.16   61.44  515.18   61.22   590.2   61.76
  755.25   61.41  801.95   61.66  817.34   61.29  920.31   61.69  950.32   61.34
  980.33   61.58  995.33   61.18 1085.36   61.21 1109.82   60.78 1166.35   60.72
#Mann= 3 , 0 , 0
       0     .15       0  248.67     .04       0  421.73      .1       0
#XS Ineff= 2 , 0
       0     188             556       0
Permanent Ineff=
       T       T
Bank Sta=248.67,421.73
XS Rating Curve= 0
Exp/Cntr=.3,.1

Type RM Length L Ch R = 1 ,837     ,463.57,467.17,466.84
BEGIN DESCRIPTION:
837.354  Survey
END DESCRIPTION:
XS GIS Cut Line= 4
     3077580.587    13809177.422     3077795.389    13809191.301
     3078023.242    13809190.802     3078744.335    13809216.098
#Sta/Elev= 30
       0   62.17   21.96   63.54   44.82   63.94   97.12   63.94  125.17   63.42
  142.21   63.78   156.3   63.72  172.27   63.49  202.33   62.35  215.25   62.27
  242.94   62.72  305.93   39.45     310   36.87  327.36   36.25  343.96   36.77
  346.45   38.42   443.1   60.88  457.37   61.48   502.4   61.16  592.45   61.28
  647.97   61.67  725.75   61.48  865.74   61.67  896.85   61.36  912.41   61.48
  927.96   61.17 1012.71   61.37 1067.95   60.89 1083.51   61.12 1164.64   60.67
#Mann= 3 , 0 , 0
       0     .15       0  242.94     .04       0  457.37      .1       0
#XS Ineff= 2 , 0
       0     191             844       0
Permanent Ineff=
       T       T
Bank Sta=242.94,457.37
XS Rating Curve= 0
Exp/Cntr=.3,.1

Type RM Length L Ch R = 1 ,370     ,75.14,75.43,75.45
BEGIN DESCRIPTION:
 370.185
END DESCRIPTION:
XS GIS Cut Line= 4
     3077566.113    13809630.053     3077771.489    13809658.319
     3078000.811    13809656.908      3078727.66    13809682.209
#Sta/Elev= 30
       0   59.88   21.59    61.1   33.87   61.26  121.66   61.78  157.86    62.5
  234.48   62.39  306.53   39.81  308.79   36.96  322.01   36.69  336.67   37.14
     341   40.37  436.64   60.47  445.74   61.52  488.36   61.58  533.39   59.63
   548.4   59.68   563.4   60.98  578.41   61.56  608.43    62.1  638.45   60.33
  683.48   59.67   713.5   59.84  759.15   60.93  848.58   61.69  863.59   61.24
   899.1   61.17   930.2   61.59 1118.74   60.56 1148.76   58.35 1163.93   58.42
#Mann= 3 , 0 , 0
       0     .15       0  234.48     .04       0  445.74      .1       0
#XS Ineff= 2 , 0
       0     197             763       0
Permanent Ineff=
       T       T
Bank Sta=234.48,445.74
XS Rating Curve= 0
Exp/Cntr=.3,.1

Type RM Length L Ch R = 1 ,295     ,28.79,26.32,26.33
BEGIN DESCRIPTION:
294.753  Survey
END DESCRIPTION:
XS GIS Cut Line= 4
     3077563.703    13809705.389      3077769.08    13809733.656
     3077998.401    13809732.244     3078725.251    13809757.546
#Sta/Elev= 30
       0   58.58   24.02   60.07   39.16   59.79  114.87   60.45  142.44   61.81
  190.58   61.52  207.31   62.33  234.48   62.39  306.53   39.81  308.79   36.96
  322.01   36.69  336.67   37.14     341   40.37  436.64   60.47  445.74   61.52
  475.76   60.87  490.77    59.7  505.78   59.56  550.81   62.16  580.82   62.06
  610.84   59.62  625.85   59.43  670.88   59.51   700.9   60.51  820.97   61.72
 1057.45   60.97 1091.13   60.41 1104.11   59.42 1151.17   57.86 1163.93   57.94
#Mann= 3 , 0 , 0
       0     .15       0  234.48     .04       0  445.74      .1       0
#XS Ineff= 2 , 0
       0     211             737       0
Permanent Ineff=
       T       T
Bank Sta=234.48,445.74
XS Rating Curve= 0
Exp/Cntr=.5,.3

Type RM Length L Ch R = 1 ,268     ,115.06,145.95,176.79
BEGIN DESCRIPTION:
 268.429
END DESCRIPTION:
XS GIS Cut Line= 4
     3077562.568    13809740.902     3077769.161    13809759.941
     3077998.483    13809758.529     3078555.039    13810014.976
#Sta/Elev= 30
       0   56.94    42.4   56.71   55.16   57.61   75.59   57.43  125.37      58
  141.96   57.75  160.61   58.31  238.06   59.21  249.87   57.57  306.53   39.81
  308.79   36.96  322.01   36.69  336.67   37.14     341   40.37  436.64   60.47
  446.72   61.08  479.75   59.74  506.02   61.09   529.3   61.32  577.71    61.1
  611.88    60.2   628.4   59.46  677.94   59.74  727.49   59.58  760.52   59.85
  855.48    59.3  886.11   59.58  909.16   59.34   942.2   59.42 1049.59   58.62
#Mann= 3 , 0 , 0
       0     .08       0  238.06     .04       0  436.64     .08       0
#XS Ineff= 2 , 0
       0     215             705       0
Permanent Ineff=
       T       T
Bank Sta=238.06,436.64
XS Rating Curve= 0
Exp/Cntr=.5,.3

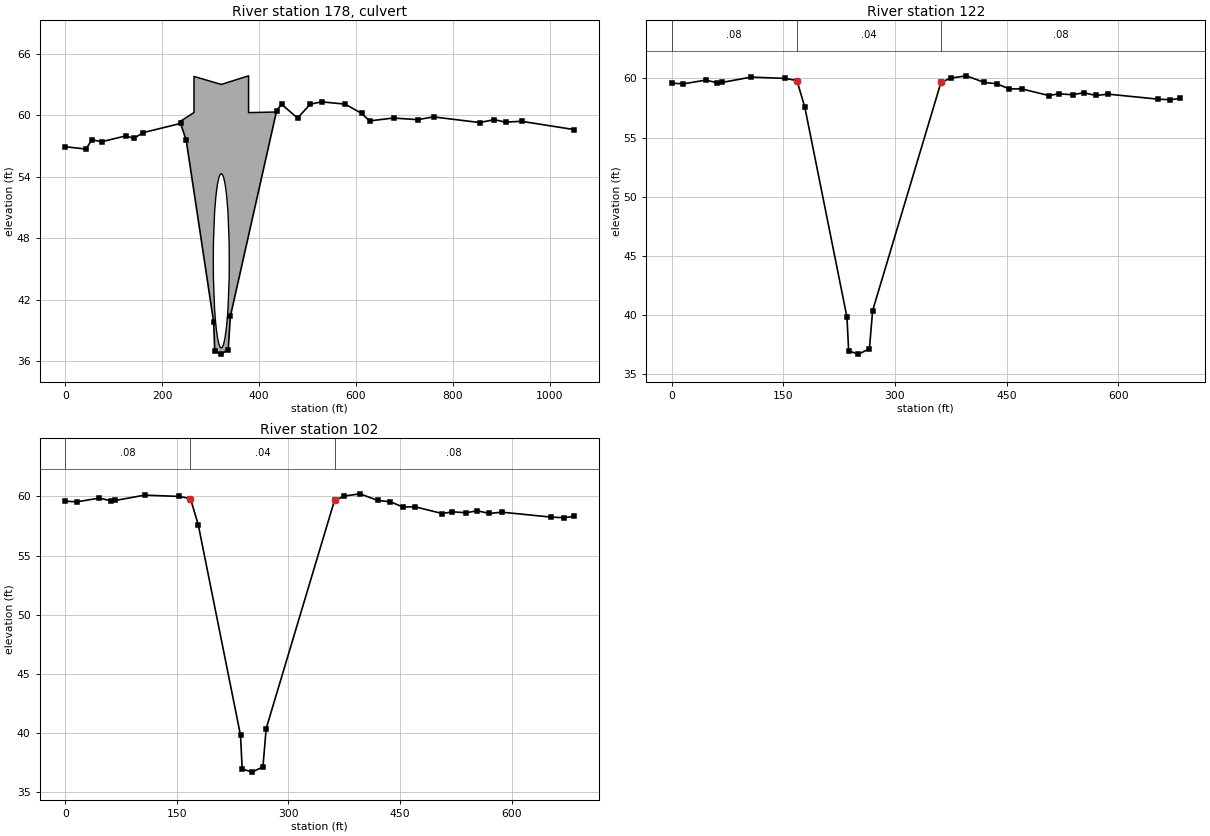
Type RM Length L Ch R = 2 ,178     ,,,
BEGIN DESCRIPTION:
Braeswood Culvert
END DESCRIPTION:
Bridge Culvert--1,0,-1,-1, 0
Deck Dist Width WeirC Skew NumUp NumDn MinLoCord MaxHiCord MaxSubmerge Is_Ogee
15,110,2.6,0, 7, 7, , , .95, 0, 0,0,,
  235.78  265.92  265.92  322.27  378.62  378.62     437
   59.36   60.28    63.8   63.02   63.86   60.27   60.33
       0       0       0       0       0       0       0
  168.29  194.91  194.91  251.26  307.61  307.61  361.89
   59.83   60.28    63.8   63.02   63.86   60.27    59.7
       0       0       0       0       0       0       0
BR Coef=-1 , 0 , 0 ,, 0 ,,,.8,-1,,0,
WSPro=,,,, 1 ,,,, 0 ,,,, 0 ,,,,-1 ,-1 ,-1 , 0 , 0 , 0 , 0 , 0
Culvert=4,17,33,130,.028,.5,1,29,1,37.3,322.27,37.3,251.26,Culvert #1  , 0 ,5
Culvert Bottom n=.028
BC Design=,, 0 ,, 0 ,,,,,,

Type RM Length L Ch R = 1 ,122     ,20,20,20
BEGIN DESCRIPTION:
 122.481
END DESCRIPTION:
XS GIS Cut Line= 4
     3077632.178    13809857.858     3077765.868    13809879.764
     3077996.999    13809943.556     3078274.329    13810076.923
#Sta/Elev= 30
       0    59.6   15.53   59.54   45.93   59.86   61.13   59.63   67.48   59.66
  106.73   60.11  152.73      60  168.29   59.82  178.87   57.57  235.53   39.81
  237.79   36.96  251.01   36.69  265.67   37.14     270   40.37  361.89   59.68
  375.25   60.03  395.88   60.22  420.19   59.66  436.83   59.55  453.48   59.11
  470.12   59.12  506.83   58.55  520.05    58.7  538.89   58.62  553.34   58.79
  569.99   58.56  586.63   58.67  653.21   58.25  669.85    58.2  682.98   58.31
#Mann= 3 , 0 , 0
       0     .08       0  168.29     .04       0  361.89     .08       0
#XS Ineff= 2 , 0
       0     145             572       0
Permanent Ineff=
       T       T
Bank Sta=168.29,361.89
XS Rating Curve= 0
Exp/Cntr=.5,.3

Type RM Length L Ch R = 1 ,102     ,0,0,0
BEGIN DESCRIPTION:
 122.481
END DESCRIPTION:
XS GIS Cut Line= 4
       3077628.9      13809877.6       3077761.6      13809899.3
       3077989.9      13809962.4       3078265.7      13810094.9
#Sta/Elev= 30
       0    59.6   15.53   59.54   45.93   59.86   61.13   59.63   67.48   59.66
  106.73   60.11  152.73      60  168.29   59.82  178.87   57.57  235.53   39.81
  237.79   36.96  251.01   36.69  265.67   37.14     270   40.37  361.89   59.68
  375.25   60.03  395.88   60.22  420.19   59.66  436.83   59.55  453.48   59.11
  470.12   59.12  506.83   58.55  520.05    58.7  538.89   58.62  553.34   58.79
  569.99   58.56  586.63   58.67  653.21   58.25  669.85    58.2  682.98   58.31
#Mann= 3 , 0 , 0
       0     .08       0  168.29     .04       0  361.89     .08       0
#XS Ineff= 2 , 0
       0     145             572       0
Permanent Ineff=
       T       T
Bank Sta=168.29,361.89
XS Rating Curve= 0
Exp/Cntr=.3,.1

Chan Stop Cuts=-1